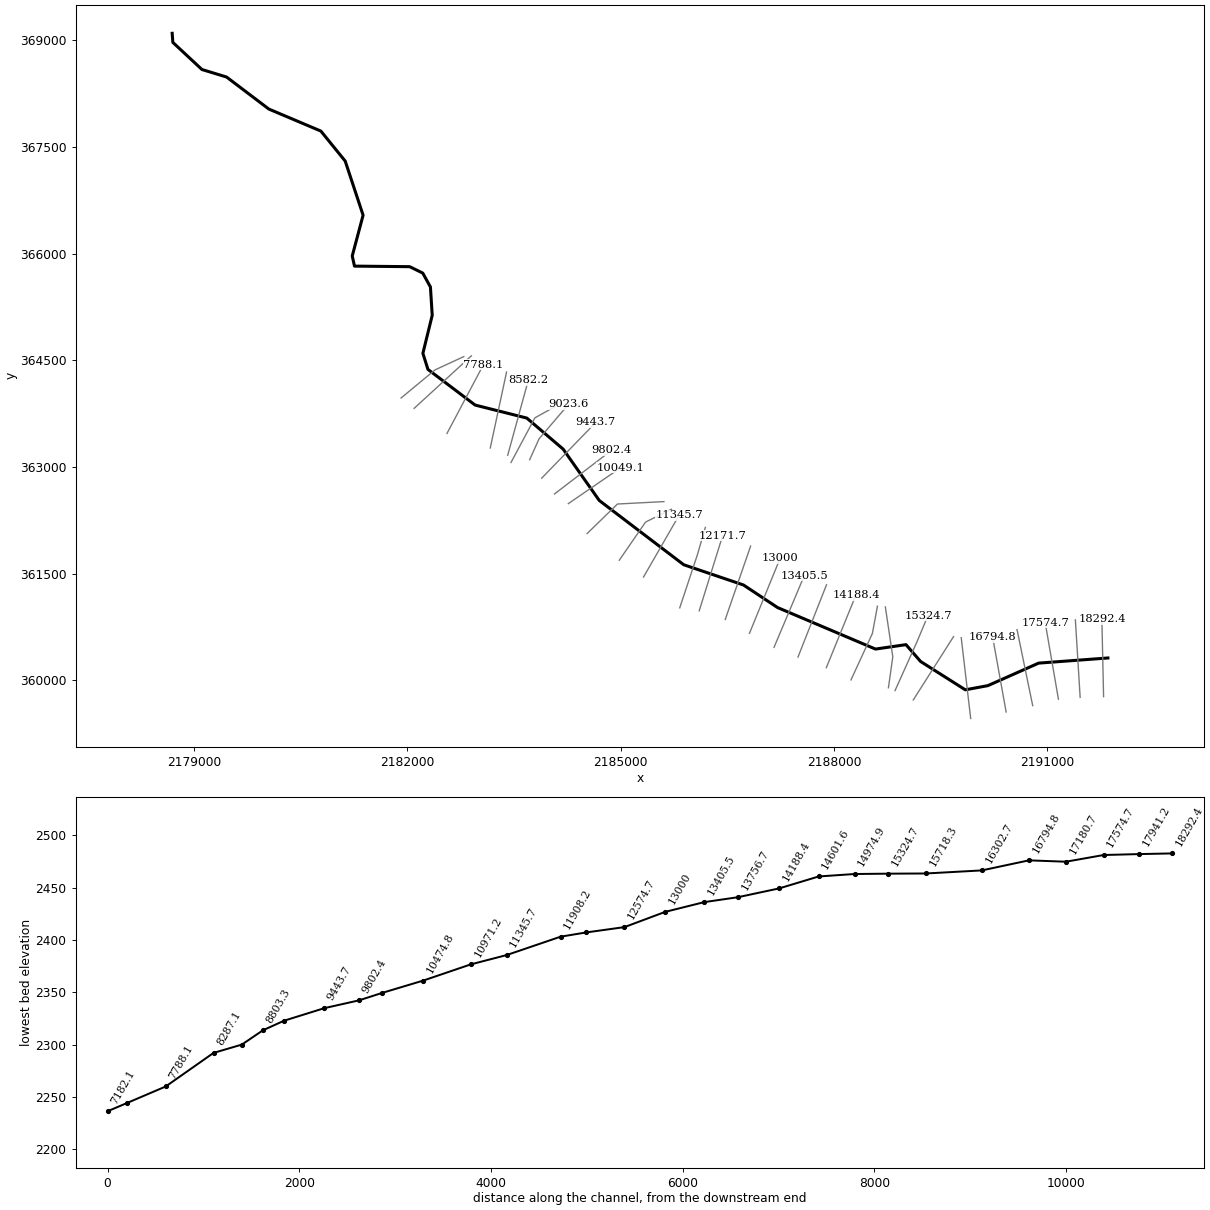
--- SlabcmpRun.prj (project) ---

Proj Title=SlabcmpRun
Current Plan=p01
Geom File=g01
Flow File=f01
Plan File=p01
DSS Export Rating Curves=0
DSS Export Rating Curve Sorted=0
DSS Export Volume Flow Curves=0
DXF OffsetX=0
DXF OffsetY=0
DXF ScaleX=0
DXF ScaleY=0

--- SlabcmpRun.p01 (plan) ---

Plan Title=Floodplain
Program Version=4.00
Geom File=g01
Flow File=f01
K Sum by GR=0
Std Step Tol=0.01
Critical Tol=0.01
Num of Std Step Trials=20
Max Error Tol=0.3
Flow Tol Ratio=0.001
Split Flow NTrial=30
Split Flow Tol=0.02
Split Flow Ratio=0.02
Log Output Level=0
Friction Slope Method=1
Unsteady Friction Slope Method=2
Unsteady Bridges Friction Slope Method=1
Global Log Level=0
CheckData=False
Run HTab=0
Run UNet=0
Run PostProcess=0
UNET Theta=0
UNET Theta Warmup=0
UNET ZTol=0
UNET ZSATol=0
UNET MxIter=0
UNET MaxInSteps=0
UNET DtIC=0
UNET DtMin=0
UNET MaxCRTS=0
UNET WFStab=0
UNET SFStab=0
UNET WFX=0
UNET SFX=0
UNET DSS MLevel=0
UNET DZMax Abort=0
UNET Convert EG Bridges=0
UNET Use Existing IB Tables=0
UNET Froude Limit=0
UNET Froude Power=0
Write IC File=0
Echo Input=False
Echo Output=False
Write Detailed=0

--- SlabcmpRun.f01 (steady flow) ---

Flow Title=NFF Regression Equation
Program Version=4.00
Number of Profiles=1
Profile Names=P100yr
River Rch & RM=SlabcmpRun,Main      ,18292.4
618.1708
River Rch & RM=SlabcmpRun,Main      ,17180.7
645.7131
River Rch & RM=SlabcmpRun,Main      ,13756.7
707.6032
River Rch & RM=SlabcmpRun,Main      ,10049.1
779.3878
River Rch & RM=SlabcmpRun,Main      ,9802.4
962.8261
River Rch & RM=SlabcmpRun,Main      ,8582.2
982.2552
River Rch & RM=SlabcmpRun,Main      ,4098.8
1090.053
River Rch & RM=SlabcmpRun,Main      ,257.9
1206.972
Boundary for River Rch & Prof#=SlabcmpRun,Main      ,1
Up Type=0
Dn Type=3
Dn Slope=0.042179

--- SlabcmpRun.g01 (geometry) ---

Geom Title=USGS 10m DEM
Program Version=4.10

River Reach=SlabcmpRun      ,Main
Reach XY= 30
     2191849.413       360315.44     2190875.502      360243.185
     2190161.273      359926.437     2189844.501      359867.843
     2189216.002      360266.063     2189010.062      360502.876
     2188581.418      360440.727     2187204.861      361024.293
     2186725.066      361341.845     2185885.555      361626.248
      2184697.48      362530.198     2184189.886      363251.968
     2183678.811      363688.628     2182952.459      363871.359
     2182288.954      364372.812     2182217.793      364598.947
     2182349.043      365133.323     2182323.797      365531.851
      2182216.23      365727.072     2182032.159      365817.365
     2181255.897      365825.145     2181224.475      365967.708
     2181377.168      366541.135     2181125.605      367302.073
     2180783.418      367723.947     2180052.168      368033.322
     2179457.663      368483.682     2179111.191      368589.466
     2178702.167      368970.822     2178692.647      369098.668

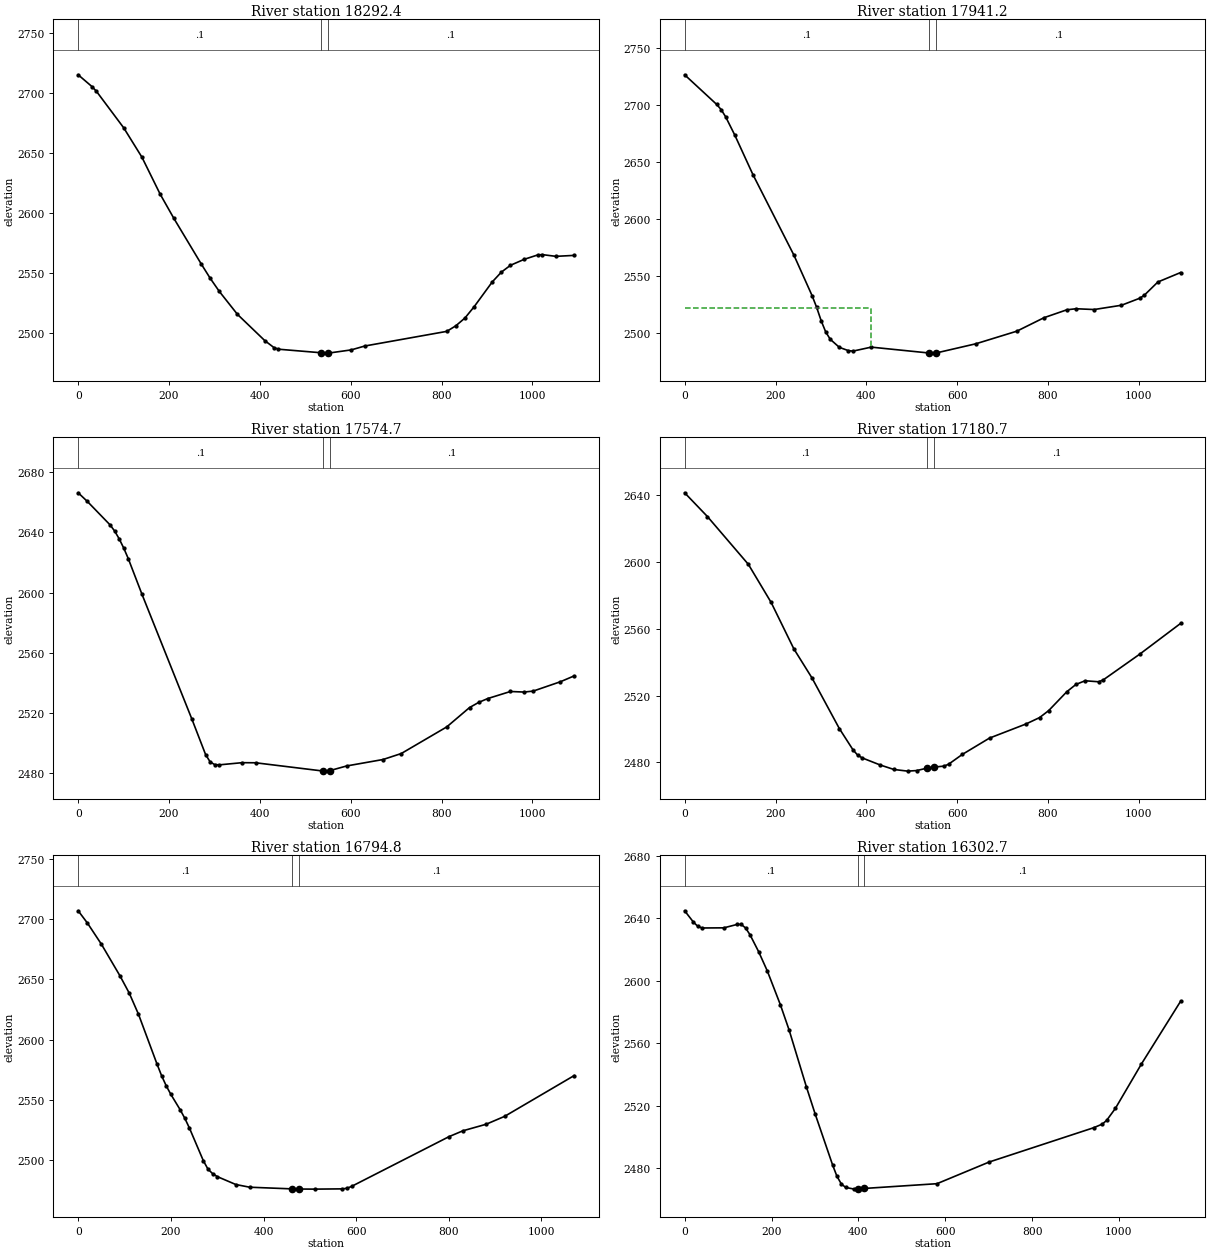
Type RM Length L Ch R = 1 ,18292.4 ,350.4,351.3,352.1
XS GIS Cut Line= 2
     2191788.608       359771.61     2191764.482      360863.343
#Sta/Elev= 30
       0 2715.44    30.1 2705.67    40.1 2701.67   100.2 2671.11   140.3 2646.58
   180.3 2615.77   210.4 2595.57   270.5 2557.55   290.5 2545.42   310.6 2534.41
   350.6  2515.2   410.8 2493.25   430.8 2487.47   440.8 2486.06   535.6 2483.06
   550.6 2482.78   601.1 2485.48   631.2 2488.74   811.5 2500.97   831.5 2505.64
   851.6 2512.16   871.6 2521.48   911.7 2542.31   931.7 2550.48   951.7 2556.19
   981.8 2561.17  1011.8 2564.87  1021.9 2565.13  1051.9 2563.69    1092 2564.49
#Mann= 3 , 0 , 0
       0      .1       0   535.6    .045       0   550.6      .1       0
Bank Sta=535.6,550.6
XS Rating Curve= 0 ,0
Exp/Cntr=0.3,0.1

Type RM Length L Ch R = 1 ,17941.2 ,364,366.5,369
XS GIS Cut Line= 2
     2191459.092      359761.662     2191391.941      360851.595
#Sta/Elev= 30
       0 2726.19    70.1 2700.38    80.2 2695.74    90.2 2689.38   110.2 2673.46
   150.3 2638.67   240.4 2568.14   280.5 2532.56   290.5 2522.33   300.6 2510.44
   310.6 2500.64   320.6 2494.23   340.6 2487.17   360.7 2484.27   370.7  2483.9
   410.8 2487.38   538.5 2482.21     551 2482.12   553.5 2482.24   641.2 2490.32
   731.3 2501.36   791.4 2513.22   841.5 2520.12   861.6 2521.04   901.6 2520.36
   961.8 2524.11  1001.8 2530.23  1011.8  2532.8  1041.9  2544.5    1092  2552.8
#Mann= 3 , 0 , 0
       0      .1       0   538.5    .045       0   553.5      .1       0
#XS Ineff= 2 , 0
          411.22 2521.56
Permanent Ineff=
       F       F
Bank Sta=538.5,553.5
XS Rating Curve= 0 ,0
Exp/Cntr=0.3,0.1

Type RM Length L Ch R = 1 ,17574.7 ,393.2,393.9,394.6
XS GIS Cut Line= 2
     2191153.704      359736.728     2190967.625      360812.757
#Sta/Elev= 30
       0 2666.39      20  2660.7    70.1 2645.07    80.2 2640.98    90.2  2635.8
   100.2 2629.64   110.2 2622.64   140.3 2598.98   250.5 2515.71   280.5 2492.26
   290.5 2487.38   300.6 2485.58   310.6 2485.42   360.7 2486.87   390.7  2486.8
   538.5 2481.33     541 2481.25   553.5 2481.55   591.1 2484.69   671.2 2488.98
   711.3 2492.95   811.5 2510.67   861.6 2523.53   881.6 2526.94   901.6 2529.52
   951.7 2534.23   981.8 2533.85  1001.8 2534.49  1061.9 2540.73    1092  2544.6
#Mann= 3 , 0 , 0
       0      .1       0   538.5    .045       0   553.5      .1       0
Bank Sta=538.5,553.5
XS Rating Curve= 0 ,0
Exp/Cntr=0.3,0.1

Type RM Length L Ch R = 1 ,17180.7 ,386.7,385.9,384.8
XS GIS Cut Line= 2
     2190792.075      359644.938     2190571.718      360714.474
#Sta/Elev= 30
       0 2641.28    50.1 2627.09   140.3 2598.48   190.4 2575.71   240.4 2547.95
   280.5 2530.48   340.6 2500.27   370.7 2487.54   380.7 2484.46   390.7 2482.76
   430.8 2478.48   460.8 2475.82   490.9 2474.84   510.9 2475.18   533.2  2476.6
   548.2 2477.24     571 2477.83   581.1 2478.97   611.1 2484.79   671.2  2494.6
   751.4 2503.02   781.4 2506.86   801.5 2511.04   841.5 2522.35   861.6  2526.7
   881.6 2528.88   911.7 2528.28   921.7 2529.41  1001.8 2544.76    1092 2563.19
#Mann= 3 , 0 , 0
       0      .1       0   533.2    .045       0   548.2      .1       0
Bank Sta=533.2,548.2
XS Rating Curve= 0 ,0
Exp/Cntr=0.3,0.1

Type RM Length L Ch R = 1 ,16794.8 ,493.3,492.1,491.2
XS GIS Cut Line= 2
     2190418.453       359555.71     2190228.809      360609.321
#Sta/Elev= 30
       0 2706.71      20 2696.51      50 2679.09      90 2652.94   110.1 2638.57
   130.1 2621.03   170.1 2579.76   180.1 2570.01   190.1 2561.64   200.1 2554.56
   220.1 2541.88   230.1 2534.84   240.1 2526.71   270.1 2499.69   280.1  2492.7
   290.2 2488.95   300.2 2486.52   340.2 2479.97   370.2 2477.73   462.4 2476.34
   477.4 2476.23   510.3 2476.15   570.3 2476.37   580.3 2476.86   590.3 2478.47
   800.4 2519.63   830.4 2524.48   880.4 2529.88   920.5 2536.45  1070.5 2570.22
#Mann= 3 , 0 , 0
       0      .1       0   462.4    .045       0   477.4      .1       0
Bank Sta=462.4,477.4
XS Rating Curve= 0 ,0
Exp/Cntr=0.3,0.1

Type RM Length L Ch R = 1 ,16302.7 ,600.3,584.4,568.6
XS GIS Cut Line= 2
     2189920.021      359465.741     2189787.189      360600.024
#Sta/Elev= 30
       0 2644.81      20 2637.63      30 2634.92    40.1 2633.82    90.2 2633.91
   120.2 2636.06   130.2 2636.11   140.2 2633.83   150.3 2629.55   170.3 2618.64
   190.3 2606.28   220.4 2584.62   240.4 2568.53   280.5 2531.83   300.5 2514.63
   340.6 2482.03   350.6 2474.76   360.6  2469.9   370.7  2467.6   390.7 2466.53
   398.3  2466.7   413.3 2466.96     581 2470.01   701.2  2483.9   941.7 2505.86
   961.7  2508.2   971.7 2510.58   991.8 2518.26  1051.9 2546.77    1142 2586.88
#Mann= 3 , 0 , 0
       0      .1       0   398.3    .045       0   413.3      .1       0
Bank Sta=398.3,413.3
XS Rating Curve= 0 ,0
Exp/Cntr=0.3,0.1

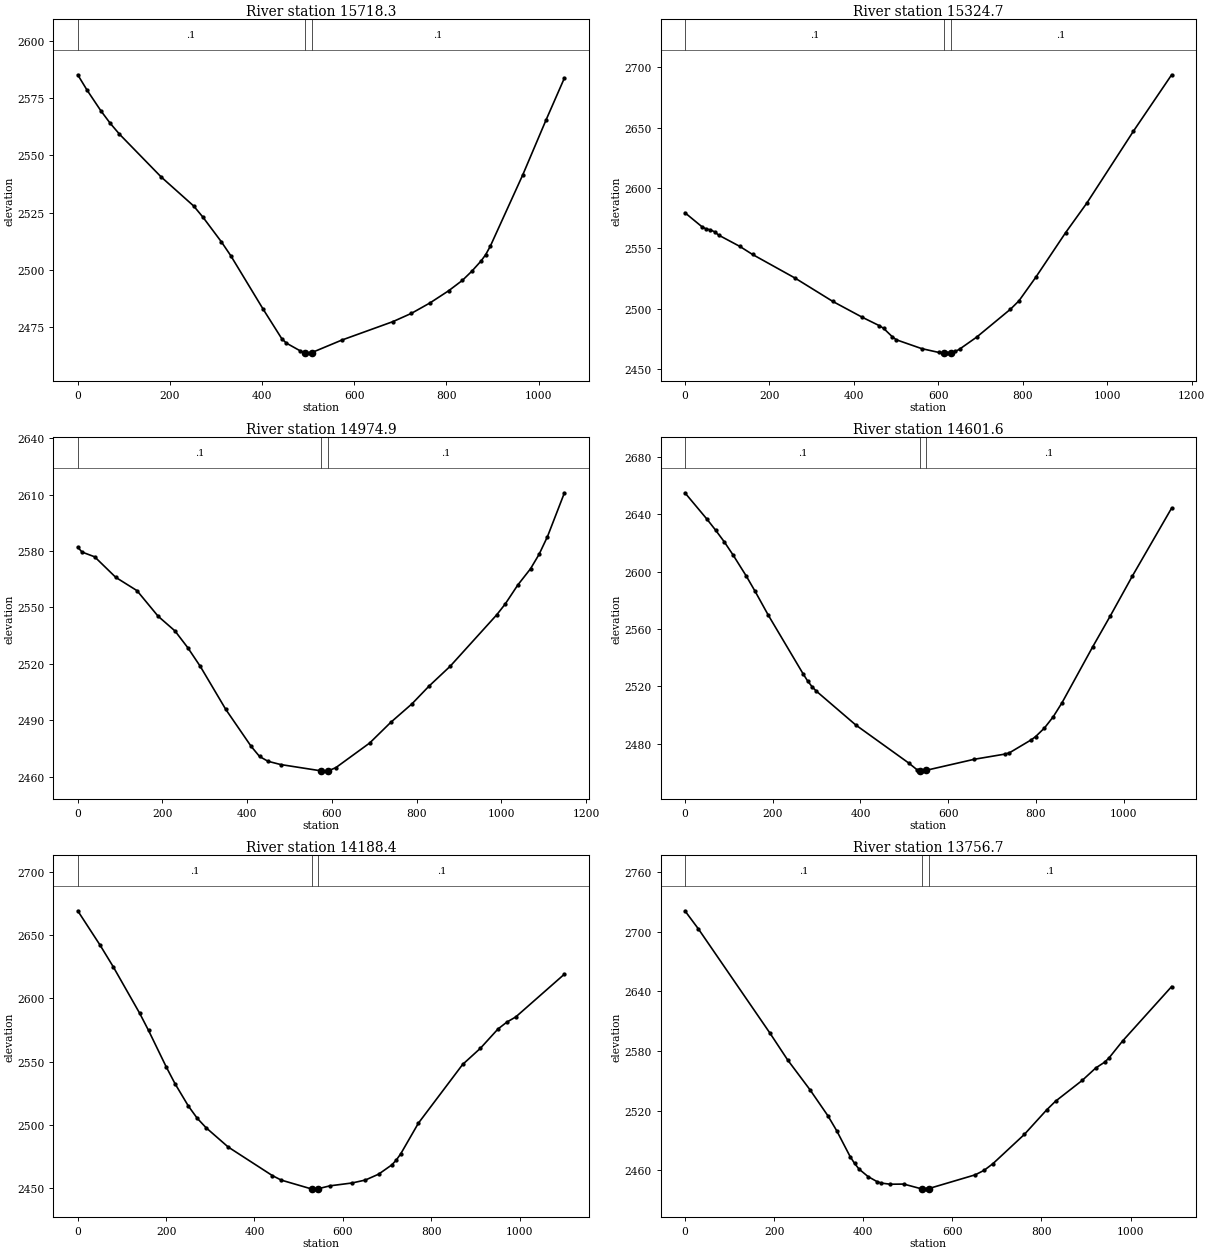
Type RM Length L Ch R = 1 ,15718.3 ,388.4,393.6,400.9
XS GIS Cut Line= 2
     2189112.913      359725.549      2189679.49      360616.682
#Sta/Elev= 30
       0 2585.22    20.1 2578.56    50.3 2569.47    70.4 2564.05    90.5 2559.29
     181 2540.59   251.4 2527.93   271.5 2523.06   311.8  2512.2   331.9 2506.22
   402.3  2482.8   442.5 2469.97   452.6 2467.98   482.7  2464.6   492.3 2463.87
   502.9  2463.6   507.3 2463.79   573.2 2469.32   683.9 2477.37   724.1 2480.99
   764.3 2485.54   804.6 2490.83   834.7 2495.42   854.8 2499.34     875 2503.84
     885 2506.59   895.1  2510.3   965.5 2541.46  1015.8 2565.34    1056 2583.84
#Mann= 3 , 0 , 0
       0      .1       0   492.3    .045       0   507.3      .1       0
Bank Sta=492.3,507.3
XS Rating Curve= 0 ,0
Exp/Cntr=0.3,0.1

Type RM Length L Ch R = 1 ,15324.7 ,339.2,349.8,358.3
XS GIS Cut Line= 3
     2188856.259      359856.584     2189164.023      360541.175
     2189319.482      360911.721
#Sta/Elev= 30
       0 2579.59      40 2568.08      50 2566.18      60 2565.43      70 2563.86
    80.1 2561.02   130.1  2551.7   160.1 2545.05   260.2 2525.63   350.3 2506.16
   420.3 2493.02   460.4 2486.12   470.4 2483.92   490.4 2477.16   500.4 2474.48
   560.4 2467.17   600.5 2464.03   614.3 2463.55   620.5 2463.42   629.3 2463.69
   640.5 2464.82   650.5 2466.77   690.5 2476.59   770.7 2499.74   790.8 2506.64
     831 2526.33   901.3 2563.07   951.5 2587.52    1062  2647.1  1152.4  2693.7
#Mann= 3 , 0 , 0
       0      .1       0   614.3    .045       0   629.3      .1       0
Bank Sta=614.3,629.3
XS Rating Curve= 0 ,0
Exp/Cntr=0.3,0.1

Type RM Length L Ch R = 1 ,14974.9 ,386,373.3,360.2
XS GIS Cut Line= 3
     2188763.476      359896.597     2188824.799      360331.556
     2188720.135      361033.633
#Sta/Elev= 30
       0 2582.08      10 2579.45    39.9 2576.92    89.8    2566   139.8 2558.96
   189.7 2545.37   229.6 2537.54   259.6 2528.71   289.5 2518.66   349.4 2495.91
   409.3 2476.28   429.3 2470.86   449.3 2468.31   479.2 2466.58   575.5  2463.2
   589.2 2463.09   590.5 2463.16   609.2 2464.91   689.2 2478.01   739.2 2489.03
   789.2 2498.84   829.2  2508.2   879.2 2518.76   989.1 2546.07  1009.1 2551.79
  1039.1 2561.98  1069.1 2570.59  1089.1 2578.17  1109.1 2587.66  1149.1  2610.9
#Mann= 3 , 0 , 0
       0      .1       0   575.5    .045       0   590.5      .1       0
Bank Sta=575.5,590.5
XS Rating Curve= 0 ,0
Exp/Cntr=0.3,0.1

Type RM Length L Ch R = 1 ,14601.6 ,412.2,413.2,414.3
XS GIS Cut Line= 3
     2188237.151      360007.053     2188537.929      360660.431
      2188609.02      361043.582
#Sta/Elev= 30
       0 2654.91      50  2636.6    69.9 2628.86    89.9  2620.6   109.9 2611.44
   139.9 2596.78   159.8 2586.24   189.8 2569.62   269.7  2528.4   279.7  2523.6
   289.7 2519.63   299.7 2516.47   389.6 2492.86   509.5  2466.5   529.5 2461.57
   535.2  2461.1   539.5 2460.75   550.2 2461.36   659.3 2469.02   729.3 2472.64
   739.3 2473.51   789.2  2482.6   799.2 2484.88   819.2 2490.83   839.2 2498.66
   859.2 2508.44   929.1 2547.44   969.1 2568.94    1019 2596.55    1109 2644.25
#Mann= 3 , 0 , 0
       0      .1       0   535.2    .045       0   550.2      .1       0
Bank Sta=535.2,550.2
XS Rating Curve= 0 ,0
Exp/Cntr=0.3,0.1

Type RM Length L Ch R = 1 ,14188.4 ,431.5,431.7,432
XS GIS Cut Line= 2
     2187890.356      360179.161     2188305.806      361199.213
#Sta/Elev= 30
       0 2669.24    50.1 2642.36    80.1 2625.16   140.2 2588.25   160.2 2574.72
   200.3 2545.88   220.3 2532.54   250.3 2515.01   270.4 2505.32   290.4 2497.85
   340.4 2482.62   440.6 2459.99   460.6 2456.45   529.7 2449.41   530.7 2449.33
   544.7  2449.7   570.7 2451.93   620.8 2454.19   650.8  2456.5   680.9 2461.15
   710.9 2468.52   720.9 2472.33   730.9  2477.2     771  2501.5   871.1 2547.87
   911.2 2560.61   951.2 2575.92   971.2 2581.32   991.3  2585.4  1101.4 2619.21
#Mann= 3 , 0 , 0
       0      .1       0   529.7    .045       0   544.7      .1       0
Bank Sta=529.7,544.7
XS Rating Curve= 0 ,0
Exp/Cntr=0.3,0.1

Type RM Length L Ch R = 1 ,13756.7 ,351.6,351.1,350.6
XS GIS Cut Line= 2
     2187491.907      360328.664     2187892.852      361344.393
#Sta/Elev= 30
       0 2720.88    30.1 2702.74   190.4 2598.08   230.4 2570.89   280.5 2540.91
   320.6 2514.81   340.6 2499.59   370.7 2473.61   380.7 2466.73   390.7 2461.04
   410.8 2453.56   430.8 2448.51   440.8 2446.96   460.8 2445.83   490.9 2445.98
   531.5  2441.1     541  2440.9   546.5 2441.38   651.2 2455.27   671.2 2459.79
   691.3 2466.61   761.4 2495.86   811.5 2520.55   831.5 2529.34   891.6 2550.36
   921.7 2562.75   941.7 2568.62   951.7 2572.97   981.8 2589.82    1092 2644.67
#Mann= 3 , 0 , 0
       0      .1       0   531.5    .045       0   546.5      .1       0
Bank Sta=531.5,546.5
XS Rating Curve= 0 ,0
Exp/Cntr=0.3,0.1

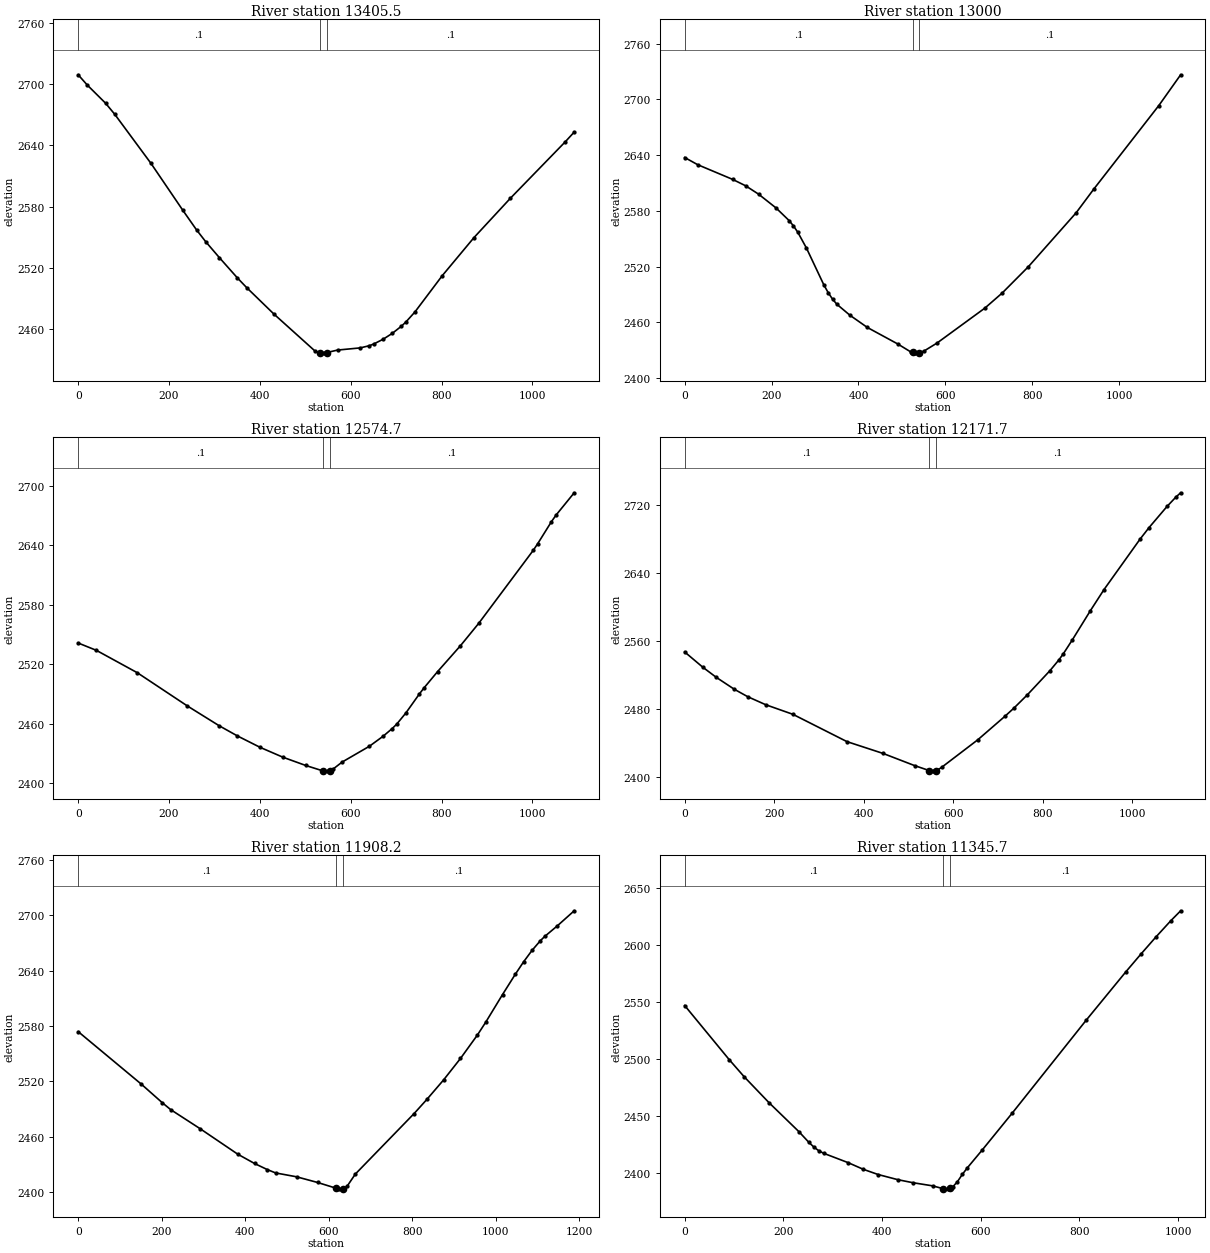
Type RM Length L Ch R = 1 ,13405.5 ,405.3,405.5,405.8
XS GIS Cut Line= 2
     2187154.881      360464.656     2187579.181      361470.854
#Sta/Elev= 30
       0 2709.17      20 2699.12    60.1  2681.4    80.2 2670.61   160.3 2622.26
   230.4 2576.27   260.5 2557.12   280.5 2545.63   310.6 2529.98   350.6 2509.92
   370.7 2500.56   430.8 2474.58     521 2438.41   532.7 2436.23     541  2436.2
   547.7  2436.8     571  2439.2   621.1 2441.34   641.2  2443.5   651.2 2445.27
   671.2 2449.78   691.3  2455.5   711.3 2462.49   721.3 2466.64   741.4 2476.57
   801.5 2512.13   871.6 2549.61   951.7 2588.15    1072 2643.28    1092 2652.95
#Mann= 3 , 0 , 0
       0      .1       0   532.7    .045       0   547.7      .1       0
Bank Sta=532.7,547.7
XS Rating Curve= 0 ,0
Exp/Cntr=0.3,0.1

Type RM Length L Ch R = 1 ,13000   ,423.9,425.3,426.4
XS GIS Cut Line= 2
     2186809.562      360662.169     2187241.427        361718.9
#Sta/Elev= 30
       0 2637.48      30 2629.72   110.2 2613.96   140.2 2607.06   170.2    2598
   210.3 2583.18   240.3 2569.64   250.3 2563.94   260.4 2557.02   280.4 2539.92
   320.4 2500.32   330.5 2491.89   340.5 2484.94   350.5 2479.45   380.5 2467.66
   420.6 2454.52   490.7 2436.73   520.7 2428.15   524.9 2427.64   530.7 2426.93
   539.9  2427.4   550.8 2429.16   580.8 2437.76     691 2475.38     731 2491.67
   791.1 2519.92   901.2 2578.03   941.3 2603.22  1091.5 2693.44  1141.6 2726.46
#Mann= 3 , 0 , 0
       0      .1       0   524.9    .045       0   539.9      .1       0
Bank Sta=524.9,539.9
XS Rating Curve= 0 ,0
Exp/Cntr=0.3,0.1

Type RM Length L Ch R = 1 ,12574.7 ,402.3,403,403.7
XS GIS Cut Line= 2
     2186468.875      360856.864     2186825.813      361888.881
#Sta/Elev= 30
       0 2541.44    40.1 2534.04   130.2 2511.48   240.4 2478.01   310.6 2458.02
   350.6 2447.81   400.7 2436.27   450.8 2426.36   500.9 2418.06   538.5 2412.63
     541 2412.35     551  2412.4   553.5 2412.89     561 2414.36   581.1 2421.48
   641.2 2437.43   671.2 2447.45   691.3 2455.22   701.3  2459.7   721.3 2470.86
   751.4 2490.26   761.4 2496.21   791.4  2512.7   841.5 2538.64   881.6 2561.12
  1001.8 2634.77  1011.8 2641.58  1041.9 2663.68  1051.9 2670.22    1092  2692.8
#Mann= 3 , 0 , 0
       0      .1       0   538.5    .045       0   553.5      .1       0
Bank Sta=538.5,553.5
XS Rating Curve= 0 ,0
Exp/Cntr=0.3,0.1

Type RM Length L Ch R = 1 ,12171.7 ,263.9,263.6,263.1
XS GIS Cut Line= 2
      2186102.79      360978.232     2186432.874      362036.629
#Sta/Elev= 30
       0 2547.08    40.3 2529.26    70.6 2517.29   110.9 2503.32   141.1 2494.53
   181.4  2485.1   241.9  2473.9   362.8 2441.83   443.5 2427.97     514  2413.7
   546.8 2407.87   554.3 2407.21   561.8 2407.92   564.4 2408.16   574.5 2411.67
   655.1 2443.93   715.6 2471.42   735.8 2481.06     766 2496.74   816.4 2525.03
   836.6 2537.77   846.6 2545.04   866.8 2561.41   907.1 2595.64   937.3 2620.21
    1018  2679.5  1038.1 2693.05  1078.4 2717.92  1098.6 2729.12  1108.7 2733.86
#Mann= 3 , 0 , 0
       0      .1       0   546.8    .045       0   561.8      .1       0
Bank Sta=546.8,561.8
XS Rating Curve= 0 ,0
Exp/Cntr=0.3,0.1

Type RM Length L Ch R = 1 ,11908.2 ,567,562.5,557.9
XS GIS Cut Line= 3
     2185829.113      361020.329     2186076.793      361764.362
      2186189.43      362151.505
#Sta/Elev= 30
       0 2573.82   150.8 2517.05   201.1  2496.9   221.2  2489.4   291.6 2468.76
     382 2441.06   422.2 2430.97   452.4 2424.44   472.5 2420.76   522.8 2416.56
     573 2410.42  616.81 2404.28   623.3 2403.38   633.4  2403.2   643.4 2406.06
   663.5 2419.51   804.3 2485.12   834.6 2500.32   874.9 2521.58   915.2 2544.75
   955.5    2570   975.7 2584.06    1016 2614.08  1046.2 2635.79  1066.4 2649.51
  1086.6 2661.89  1106.7 2672.46  1116.8 2676.93    1147 2688.41  1187.4 2704.74
#Mann= 3 , 0 , 0
       0      .1       0  616.81    .045       0   633.4      .1       0
Bank Sta=616.81,633.4
XS Rating Curve= 0 ,0
Exp/Cntr=0.3,0.1

Type RM Length L Ch R = 1 ,11345.7 ,376.2,374.5,372.6
XS GIS Cut Line= 2
     2185319.769      361453.243     2185821.062      362324.403
#Sta/Elev= 30
       0 2546.71    90.5  2499.1   120.6 2484.21   170.9 2461.49   231.2 2436.19
   251.3 2426.86   261.3 2422.76   271.4 2419.41   281.4 2417.12   331.7 2408.79
   361.8 2403.06     392 2398.46   432.2 2393.91   462.3 2391.29   502.6 2388.51
   523.4 2386.08   532.7 2385.64   538.4 2386.62   542.8 2387.38   552.8 2392.18
   562.8 2398.63   572.9 2404.35   603.1 2420.01   663.4  2452.1   814.1 2534.04
   894.5 2576.49   924.7 2591.87   954.8 2606.72     985    2621  1005.1 2629.79
#Mann= 3 , 0 , 0
       0      .1       0   523.4    .045       0   538.4      .1       0
Bank Sta=523.4,538.4
XS Rating Curve= 0 ,0
Exp/Cntr=0.3,0.1

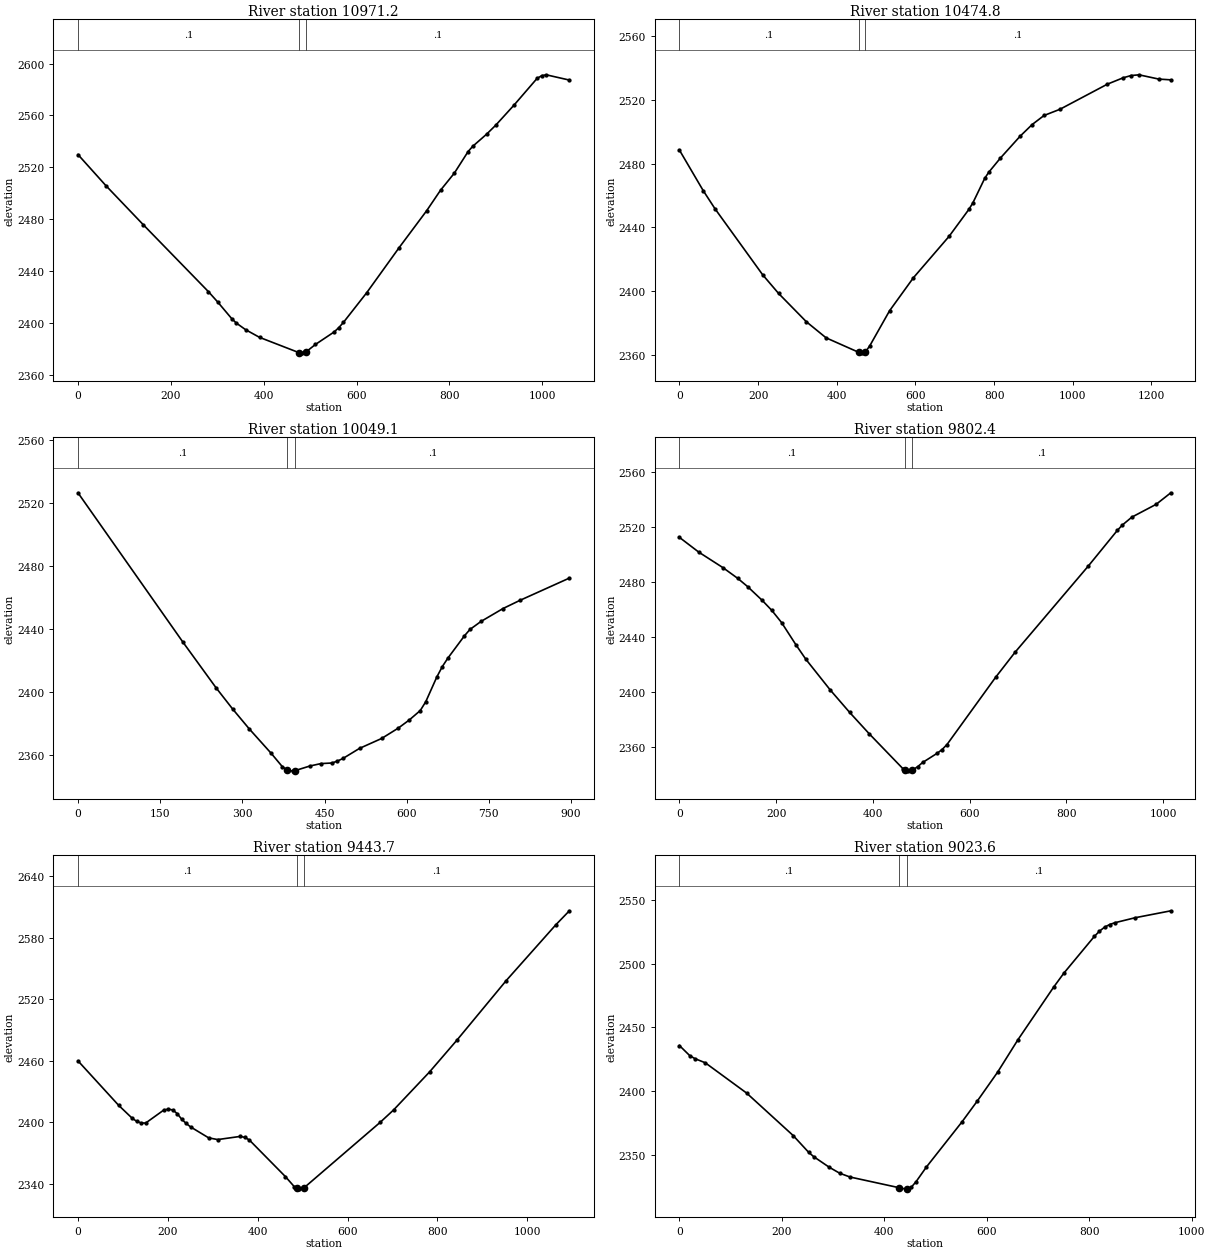
Type RM Length L Ch R = 1 ,10971.2 ,500.8,496.4,492
XS GIS Cut Line= 3
     2184978.995      361689.604     2185348.863      362226.569
     2185713.098      362406.809
#Sta/Elev= 30
       0 2529.83    60.2 2505.86   140.4 2475.83   280.9 2424.16   300.9 2416.18
     331 2403.39   341.1  2399.9   361.1  2394.8   391.2 2388.87   475.9 2377.12
   481.5 2376.73   490.9 2377.59   511.6 2383.45   551.7 2393.04   561.7 2396.34
   571.8 2400.43   621.9  2423.3   691.7 2458.05   751.1 2486.56   780.9 2502.33
   810.6 2515.48   840.4 2532.19   850.3 2536.21     880  2545.5   899.8 2552.46
   939.5 2568.08     989 2588.61   998.9 2590.66  1008.8 2591.33  1058.4 2587.29
#Mann= 3 , 0 , 0
       0      .1       0   475.9    .045       0   490.9      .1       0
Bank Sta=475.9,490.9
XS Rating Curve= 0 ,0
Exp/Cntr=0.3,0.1

Type RM Length L Ch R = 1 ,10474.8 ,429.5,425.7,421.8
XS GIS Cut Line= 3
     2184527.464      362065.308     2184953.657      362480.236
     2185607.027      362514.031
#Sta/Elev= 30
       0 2488.54    60.5 2463.11    90.7 2451.66   211.7 2410.34     252  2398.7
   322.6 2380.95     373 2370.82   455.8 2361.76   463.8 2361.25   470.8    2362
   473.8 2362.32   483.9 2365.82   534.3 2387.82   594.8 2408.48   685.4  2434.4
   735.7 2451.28   745.8 2455.31     776 2470.73   786.1 2474.53   816.2 2483.57
   866.6 2497.33   896.8 2504.54     927 2510.21   967.2 2514.07    1088 2529.84
  1128.3 2533.85  1148.4 2535.25  1168.5 2535.69  1218.9 2533.01  1249.1 2532.55
#Mann= 3 , 0 , 0
       0      .1       0   455.8    .045       0   470.8      .1       0
Bank Sta=455.8,470.8
XS Rating Curve= 0 ,0
Exp/Cntr=0.3,0.1

Type RM Length L Ch R = 1 ,10049.1 ,245.5,246.7,247.9
XS GIS Cut Line= 2
     2184262.737      362485.868     2185002.472      362992.793
#Sta/Elev= 30
       0 2526.66   191.4 2431.71   251.9 2402.64   282.1 2389.16   312.4 2376.51
   352.7 2360.85   372.8 2352.45   381.7 2350.21     393 2349.55   396.7 2349.93
   423.2  2352.8   443.3 2354.34   463.5 2354.72   473.6 2355.96   483.6  2357.6
   513.9 2364.03   554.2 2370.33   584.4 2376.88   604.6 2382.08   624.7 2388.09
   634.8 2393.76   654.9 2409.44     665  2416.1   675.1 2421.47   705.3 2435.64
   715.4 2439.71   735.6 2444.81   775.8 2453.03   806.1 2458.14   896.8 2472.39
#Mann= 3 , 0 , 0
       0      .1       0   381.7    .045       0   396.7      .1       0
Bank Sta=381.7,396.7
XS Rating Curve= 0 ,0
Exp/Cntr=0.3,0.1

Type RM Length L Ch R = 1 ,9802.4  ,355.2,358.7,361.9
XS GIS Cut Line= 2
     2184067.477      362621.048     2184874.133      363238.127
#Sta/Elev= 30
       0  2512.7    40.2 2501.89    90.5  2490.5   120.7 2482.77   140.8 2476.86
     171 2466.83   191.1 2459.42   211.2 2450.58   241.3 2434.15   261.4 2423.82
   311.7 2401.49     352 2385.05   392.2 2369.57   462.6 2343.86   466.5 2343.25
   472.6  2342.3   481.5 2343.04   492.7  2345.6   502.8 2348.62     533 2355.36
     543 2358.05   553.1 2361.69   653.6  2410.7   693.8 2428.96   844.7  2491.6
     905  2517.7   915.1 2521.55   935.2 2527.45   985.4 2536.78  1015.6 2545.16
#Mann= 3 , 0 , 0
       0      .1       0   466.5    .045       0   481.5      .1       0
Bank Sta=466.5,481.5
XS Rating Curve= 0 ,0
Exp/Cntr=0.3,0.1

Type RM Length L Ch R = 1 ,9443.7  ,418.7,420.1,421.6
XS GIS Cut Line= 2
     2183887.451      362843.012     2184648.966      363627.552
#Sta/Elev= 30
       0 2459.98    90.3 2416.72   120.4 2404.11   130.4 2401.08   140.4 2399.46
   150.5 2399.31   190.6 2411.92   200.6 2412.91   210.6 2412.13   220.7 2408.64
   230.7 2403.12   240.7 2398.96   250.8 2395.52   290.9 2384.88     311 2383.24
   361.1 2386.32   371.1 2385.42   381.2 2382.87   461.4 2347.21   481.5 2337.24
   488.4 2335.64   491.5 2334.92   503.4 2336.37   672.1 2399.91   702.2 2412.07
   782.4 2449.21   842.6 2479.84   952.9 2538.24  1063.2 2592.59  1093.4 2606.27
#Mann= 3 , 0 , 0
       0      .1       0   488.4    .045       0   503.4      .1       0
Bank Sta=488.4,503.4
XS Rating Curve= 0 ,0
Exp/Cntr=0.3,0.1

Type RM Length L Ch R = 1 ,9023.6  ,215.5,220.4,225.3
XS GIS Cut Line= 3
     2183718.783       363102.66     2183851.296      363397.135
     2184264.614      363880.851
#Sta/Elev= 30
       0 2435.75    20.2  2427.8    30.3 2425.45    50.5 2422.18   131.2  2398.4
     222 2365.05   252.3 2351.85   262.4 2348.36   292.6 2340.09   312.8 2335.44
   332.9 2332.45   428.4 2324.08   442.2 2322.92   443.4 2323.07   452.2  2324.2
   462.1 2328.82     482  2340.2   551.6 2375.74   581.4 2392.07   621.2 2414.83
   660.9 2440.32   730.5 2481.59   750.4 2492.56     810 2521.47     820 2525.59
   829.9 2528.72   839.9 2530.82   849.8  2532.2   889.6 2536.15   959.2 2541.58
#Mann= 3 , 0 , 0
       0      .1       0   428.4    .045       0   443.4      .1       0
Bank Sta=428.4,443.4
XS Rating Curve= 0 ,0
Exp/Cntr=0.3,0.1

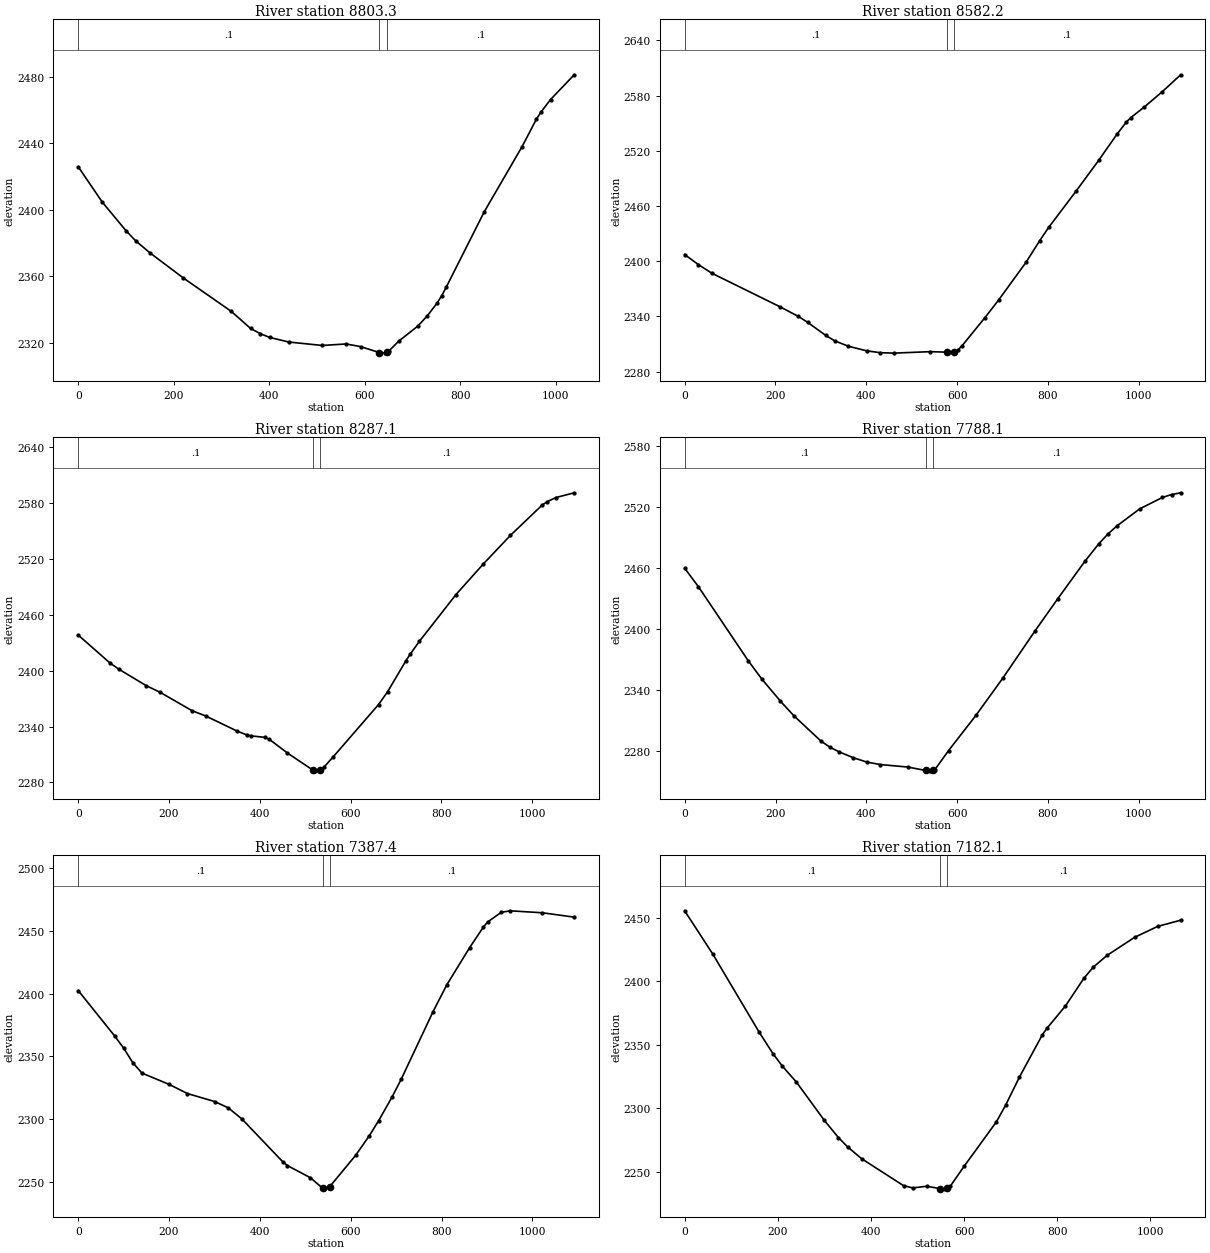
Type RM Length L Ch R = 1 ,8803.3  ,215.9,221.1,226
XS GIS Cut Line= 3
       2183456.7      363064.378     2183792.401       363691.61
     2184078.042      363850.627
#Sta/Elev= 30
       0 2425.93    50.1 2404.75   100.2  2387.4   120.2 2381.39   150.3 2374.09
   220.4 2358.93   320.6 2338.88   360.7 2328.67   380.8 2325.54   400.8 2323.24
   440.9 2320.47     511  2318.4   561.1 2319.31   591.2  2317.7   630.5 2314.15
   641.3 2313.79   645.5 2314.44   651.3 2315.34   671.3 2321.05   711.4 2330.16
   731.2 2336.36     751 2343.78     761 2348.31   770.9 2353.69   850.1 2398.84
   929.4 2438.09   959.1 2454.48     969 2458.87   988.8 2466.35  1038.3 2481.23
#Mann= 3 , 0 , 0
       0      .1       0   630.5    .045       0   645.5      .1       0
Bank Sta=630.5,645.5
XS Rating Curve= 0 ,0
Exp/Cntr=0.3,0.1

Type RM Length L Ch R = 1 ,8582.2  ,293.9,295.1,296.4
XS GIS Cut Line= 2
     2183410.352      363165.523     2183699.487      364218.801
#Sta/Elev= 30
       0 2407.19    30.1 2396.32    60.1 2386.85   210.4 2350.32   250.5 2339.94
   270.6 2333.63   310.6 2319.31   330.7 2313.36   360.7 2307.53   400.8 2302.57
   430.9 2300.55     461 2300.07   541.1 2301.67   577.5 2301.11   592.5 2301.27
   601.2 2303.23   611.2 2308.27   661.4 2338.72   691.4 2357.81   751.5  2398.6
   781.6 2422.11   801.6 2436.69   861.8 2476.04   911.9 2509.69     952 2537.99
     972 2550.78     982 2555.84  1012.1  2567.5  1052.2  2584.4  1092.2 2602.56
#Mann= 3 , 0 , 0
       0      .1       0   577.5    .045       0   592.5      .1       0
Bank Sta=577.5,592.5
XS Rating Curve= 0 ,0
Exp/Cntr=0.3,0.1

Type RM Length L Ch R = 1 ,8287.1  ,505.2,499,492.7
XS GIS Cut Line= 2
      2183165.04      363267.558     2183394.149      364335.762
#Sta/Elev= 30
       0 2438.23    70.2 2408.12    90.2 2401.38   150.3 2383.78   180.4 2376.77
   250.6 2357.05   280.6  2351.4   350.8 2334.94   370.8 2331.17   380.9 2329.98
   410.9  2328.4     421 2326.27     461 2311.53   517.6 2293.04   521.2 2292.13
   532.6 2293.09   541.2 2296.34   561.3 2307.25   661.5 2363.56   681.6 2377.41
   721.6 2410.38   731.7 2417.96   751.7 2431.56   831.9 2481.53     892 2514.31
   952.2 2545.29  1022.3 2577.87  1032.4 2581.21  1052.4 2585.89  1092.5 2590.92
#Mann= 3 , 0 , 0
       0      .1       0   517.6    .045       0   532.6      .1       0
Bank Sta=517.6,532.6
XS Rating Curve= 0 ,0
Exp/Cntr=0.3,0.1

Type RM Length L Ch R = 1 ,7788.1  ,408.4,400.7,393
XS GIS Cut Line= 2
     2182556.708      363472.691     2183068.175      364437.504
#Sta/Elev= 30
       0 2459.48    30.1 2441.43   140.3  2368.3   170.3 2350.28   210.4 2329.06
   240.4 2314.46   300.6 2289.36   320.6 2283.39   340.6 2278.89   370.7 2273.32
   400.7 2268.99   430.8  2266.5   490.9 2264.08   531.1 2260.67     541 2260.05
   546.1 2260.85     551 2261.61   581.1 2280.25   641.2 2314.78   701.3 2351.94
   771.4 2397.86   821.5 2429.52   881.6 2466.49   911.7 2483.43   931.7    2493
   951.7 2501.03  1001.8 2517.78  1051.9 2529.04    1072 2531.89    1092 2533.58
#Mann= 3 , 0 , 0
       0      .1       0   531.1    .045       0   546.1      .1       0
Bank Sta=531.1,546.1
XS Rating Curve= 0 ,0
Exp/Cntr=0.3,0.1

Type RM Length L Ch R = 1 ,7387.4  ,206.5,205.3,204.1
XS GIS Cut Line= 2
     2182094.605      363825.082     2182899.271      364563.308
#Sta/Elev= 30
       0 2402.46    80.2 2366.32   100.2 2356.51   120.2 2345.04   140.3 2336.74
   200.4 2327.72   240.4 2320.47   300.6 2314.06   330.6 2309.04   360.7 2300.14
   450.8 2265.97   460.8 2263.12   510.9  2253.5   538.5 2245.04     541 2244.38
   553.5  2246.2   611.1  2271.4   641.2 2287.02   661.2 2298.67   691.3 2317.86
   711.3 2331.94   781.4  2385.7   811.5 2406.93   861.6 2436.45   891.6 2452.69
   901.6 2457.06   931.7 2464.74   951.7  2465.9  1021.9 2464.36    1092 2460.88
#Mann= 3 , 0 , 0
       0      .1       0   538.5    .045       0   553.5      .1       0
Bank Sta=538.5,553.5
XS Rating Curve= 0 ,0
Exp/Cntr=0.3,0.1

Type RM Length L Ch R = 1 ,7182.1  ,204.1,193.7,183.4
XS GIS Cut Line= 3
     2181911.287       363970.98     2182388.839      364366.252
     2182792.837      364552.774
#Sta/Elev= 30
       0 2455.49      60 2421.66     160 2359.91     190 2342.83     210 2333.12
     240 2320.63     300 2290.46     330 2277.04     350 2269.61     380 2260.35
   469.9 2239.13   489.9 2237.34   519.9 2238.68   547.9 2236.81   559.9  2236.4
   562.9 2237.02   569.9 2238.47   599.9 2254.32   669.4  2289.4   689.1 2302.47
   718.8  2324.6   768.2 2358.02   778.1 2363.13   817.7 2380.63   857.2 2402.41
     877 2411.02   906.7 2420.34     966  2434.6  1015.4  2443.2  1064.9  2448.1
#Mann= 3 , 0 , 0
       0      .1       0   547.9    .045       0   562.9      .1       0
Bank Sta=547.9,562.9
XS Rating Curve= 0 ,0
Exp/Cntr=0.3,0.1