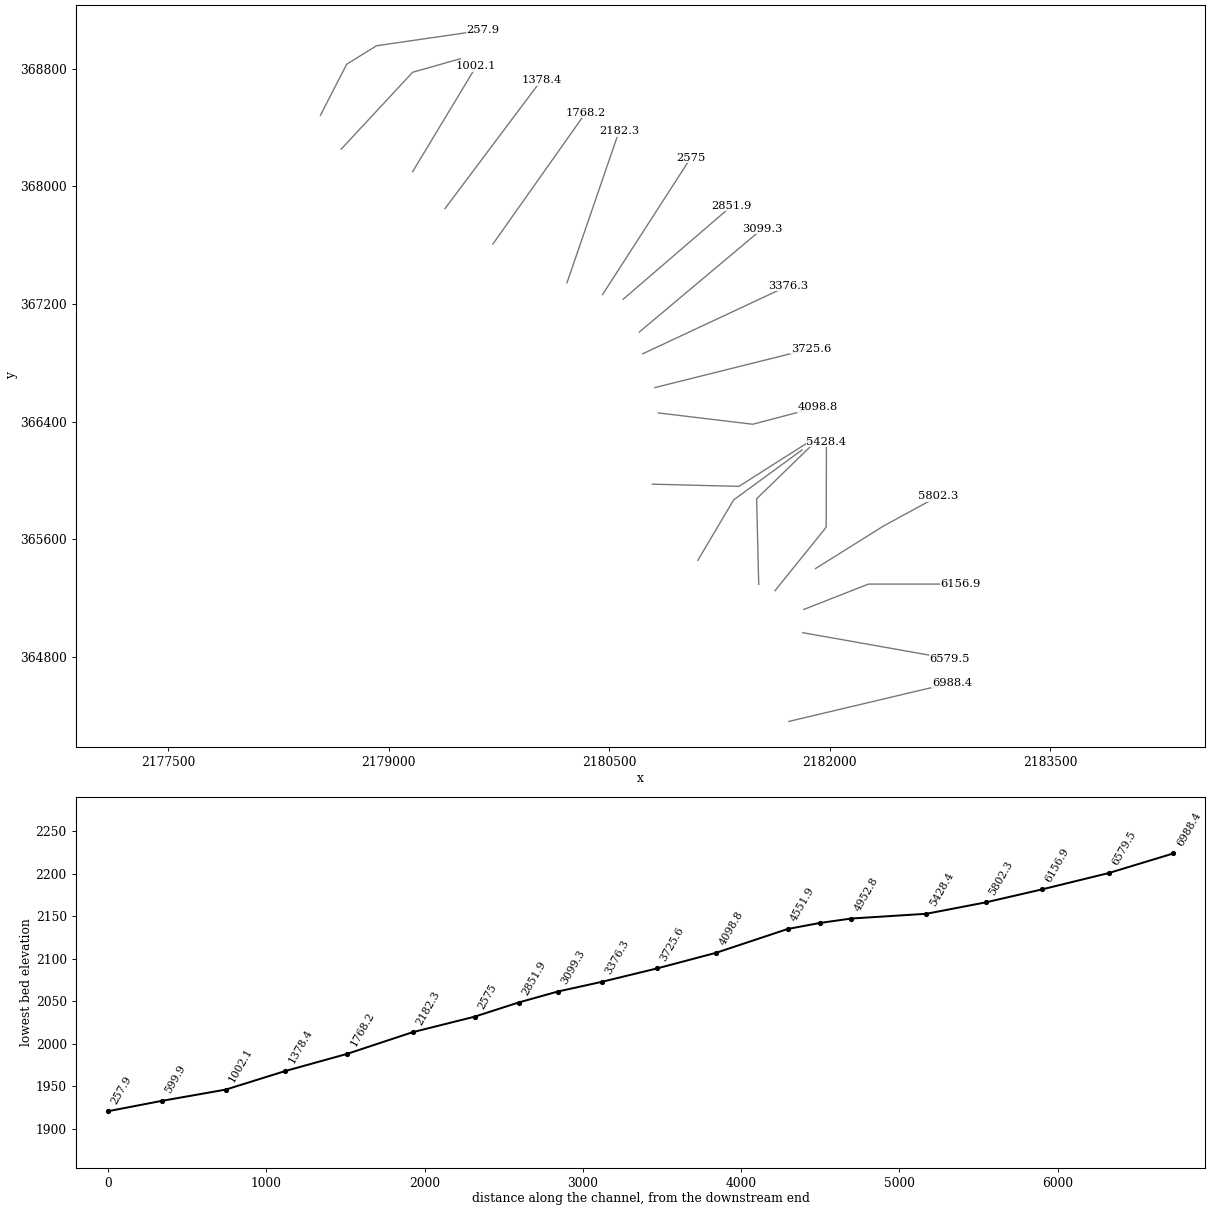
HEC-RAS study SlabcmpRun.prj: SlabcmpRun

--- SlabcmpRun.g01 (geometry) --- (continued)

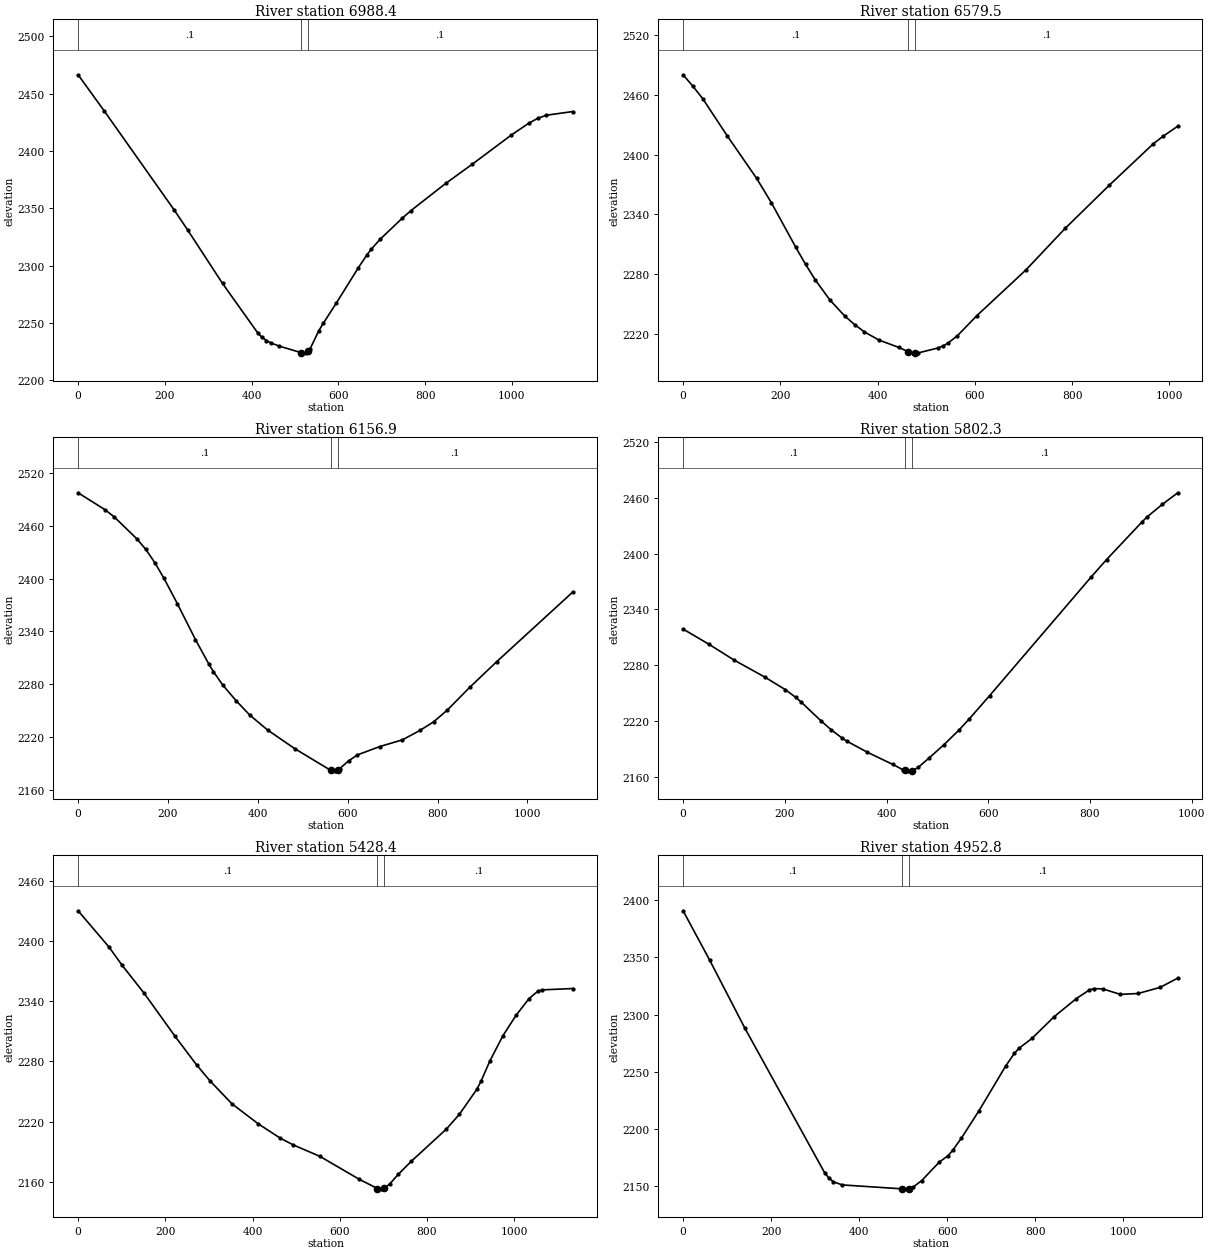
Type RM Length L Ch R = 1 ,6988.4  ,418.2,408.9,399.7
XS GIS Cut Line= 2
      2181722.07      364360.564     2182831.789      364623.574
#Sta/Elev= 30
       0 2466.52    60.6 2434.77     222 2348.27   252.3 2331.24     333 2284.39
   413.8 2241.41   423.9  2237.4     434  2234.6   444.1 2232.56   464.3 2229.69
   513.9 2224.06   524.8 2223.61   528.9 2225.14   534.9 2227.39   555.1 2243.26
   565.2 2249.62   595.5 2267.36   645.9 2298.02   666.1 2309.45   676.2 2314.49
   696.4 2322.99   746.8 2341.18     767 2347.88   847.8  2371.8   908.3 2388.34
   999.2 2414.06  1039.5 2424.34  1059.7 2428.56  1079.9 2431.27  1140.5 2434.47
#Mann= 3 , 0 , 0
       0      .1       0   513.9    .045       0   528.9      .1       0
Bank Sta=513.9,528.9
XS Rating Curve= 0 ,0
Exp/Cntr=0.3,0.1

Type RM Length L Ch R = 1 ,6579.5  ,418.6,422.6,426.5
XS GIS Cut Line= 2
     2181816.354      364964.168     2182817.605      364786.673
#Sta/Elev= 30
       0 2480.28    20.1 2468.82    40.3 2456.33    90.6 2419.02     151 2376.31
   181.2 2351.92   231.6 2306.97   251.7 2289.83   271.8 2274.08     302 2253.83
   332.2  2237.9   352.4 2229.31   372.5 2221.92   402.7 2213.67     443 2206.36
   462.3  2202.1   473.2 2200.54   477.3 2200.63   483.3 2200.75   523.5 2205.64
   533.6 2207.58   543.7 2210.28   563.8 2217.95   604.1 2238.28   704.8 2284.15
   785.3 2325.83   875.9 2369.15   966.5 2410.87   986.7 2418.48  1016.9 2428.62
#Mann= 3 , 0 , 0
       0      .1       0   462.3    .045       0   477.3      .1       0
Bank Sta=462.3,477.3
XS Rating Curve= 0 ,0
Exp/Cntr=0.3,0.1

Type RM Length L Ch R = 1 ,6156.9  ,341.9,354.6,367.1
XS GIS Cut Line= 3
     2181823.864      365121.878     2182263.199      365294.608
     2182892.162      365294.608
#Sta/Elev= 30
       0 2497.44    60.3 2478.09    80.4 2470.05   130.6 2445.23   150.7 2433.12
   170.8 2418.02   190.8 2400.52     221  2371.4   261.2 2330.66   291.3  2302.6
   301.3 2294.22   321.4 2279.39   351.5 2261.37   381.7 2245.14   421.8 2227.99
   482.1 2206.87   562.7 2182.04   571.9 2181.29   577.7 2182.83   581.9 2183.94
   601.9 2192.94   621.8 2199.74   671.7 2209.26   721.7 2216.78   761.6 2227.74
   791.5 2237.35   821.5 2250.51   871.4 2276.33   931.3  2305.4    1101  2384.7
#Mann= 3 , 0 , 0
       0      .1       0   562.7    .045       0   577.7      .1       0
Bank Sta=562.7,577.7
XS Rating Curve= 0 ,0
Exp/Cntr=0.3,0.1

Type RM Length L Ch R = 1 ,5802.3  ,351.1,373.9,396.9
XS GIS Cut Line= 3
     2181902.719      365399.748     2182362.884      365687.852
     2182740.084      365893.531
#Sta/Elev= 30
       0 2318.82    50.3 2302.66   100.5 2285.41   160.9 2267.12   201.1 2253.66
   221.2 2245.48   231.2 2240.83   271.5 2219.93   291.6 2210.35   311.7 2202.03
   321.7 2198.42   361.9 2186.48   412.2 2173.33   432.3 2167.56   435.8 2167.05
   442.4 2166.08   450.8  2166.7   452.4 2166.82   462.5 2170.18   482.6 2179.68
   512.8 2194.43   542.9 2210.49   562.9 2222.39   602.9 2247.35   802.7 2375.02
   832.7 2393.56   902.6 2434.14   912.6 2439.52   942.6 2453.03   972.6 2465.33
#Mann= 3 , 0 , 0
       0      .1       0   435.8    .045       0   450.8      .1       0
Bank Sta=435.8,450.8
XS Rating Curve= 0 ,0
Exp/Cntr=0.3,0.1

Type RM Length L Ch R = 1 ,5428.4  ,474.9,475.6,476.2
XS GIS Cut Line= 3
     2181628.174      365249.978     2181975.942      365681.373
     2181977.819      366261.521
#Sta/Elev= 30
       0 2430.15    70.5  2394.2   100.8 2375.88   151.1 2348.15   221.6 2305.42
     272 2276.37   302.2 2260.74   352.6 2237.81   413.1  2217.8   463.4 2203.56
   493.7 2196.72   554.1 2185.45   644.1 2162.67   686.5  2153.3   694.2 2152.71
   701.5 2153.62   714.2 2157.68   734.2 2167.48   764.2 2180.52   844.2 2212.46
   874.2 2227.24   914.2 2252.09   924.2 2260.52   944.2  2280.4   974.2 2305.67
  1004.2  2325.9  1034.2 2342.71  1054.2 2349.96  1064.2 2351.35  1134.3 2352.68
#Mann= 3 , 0 , 0
       0      .1       0   686.5    .045       0   701.5      .1       0
Bank Sta=686.5,701.5
XS Rating Curve= 0 ,0
Exp/Cntr=0.3,0.1

Type RM Length L Ch R = 1 ,4952.8  ,211.5,198.8,186.2
XS GIS Cut Line= 3
     2181517.135      365292.416     2181502.812      365874.756
     2181891.454      366252.133
#Sta/Elev= 30
       0  2390.8    60.3 2347.68   140.6 2287.88   321.4 2161.64   331.4 2156.75
   341.5 2153.55   361.6  2150.8   497.5 2147.36   502.2 2147.11   512.5 2147.35
   522.3 2148.77   542.3 2154.59   582.5 2170.87   602.6 2176.48   612.6 2181.05
   632.7 2191.84   672.8 2215.91     733  2254.8   753.1 2266.11   763.1 2270.31
   793.2 2279.19   843.3 2298.07   893.5 2313.88   923.6 2321.57   933.6 2322.67
   953.7 2322.46   993.8 2317.63    1034 2318.41  1084.1 2323.74  1124.2 2331.86
#Mann= 3 , 0 , 0
       0      .1       0   497.5    .045       0   512.5      .1       0
Bank Sta=497.5,512.5
XS Rating Curve= 0 ,0
Exp/Cntr=0.3,0.1

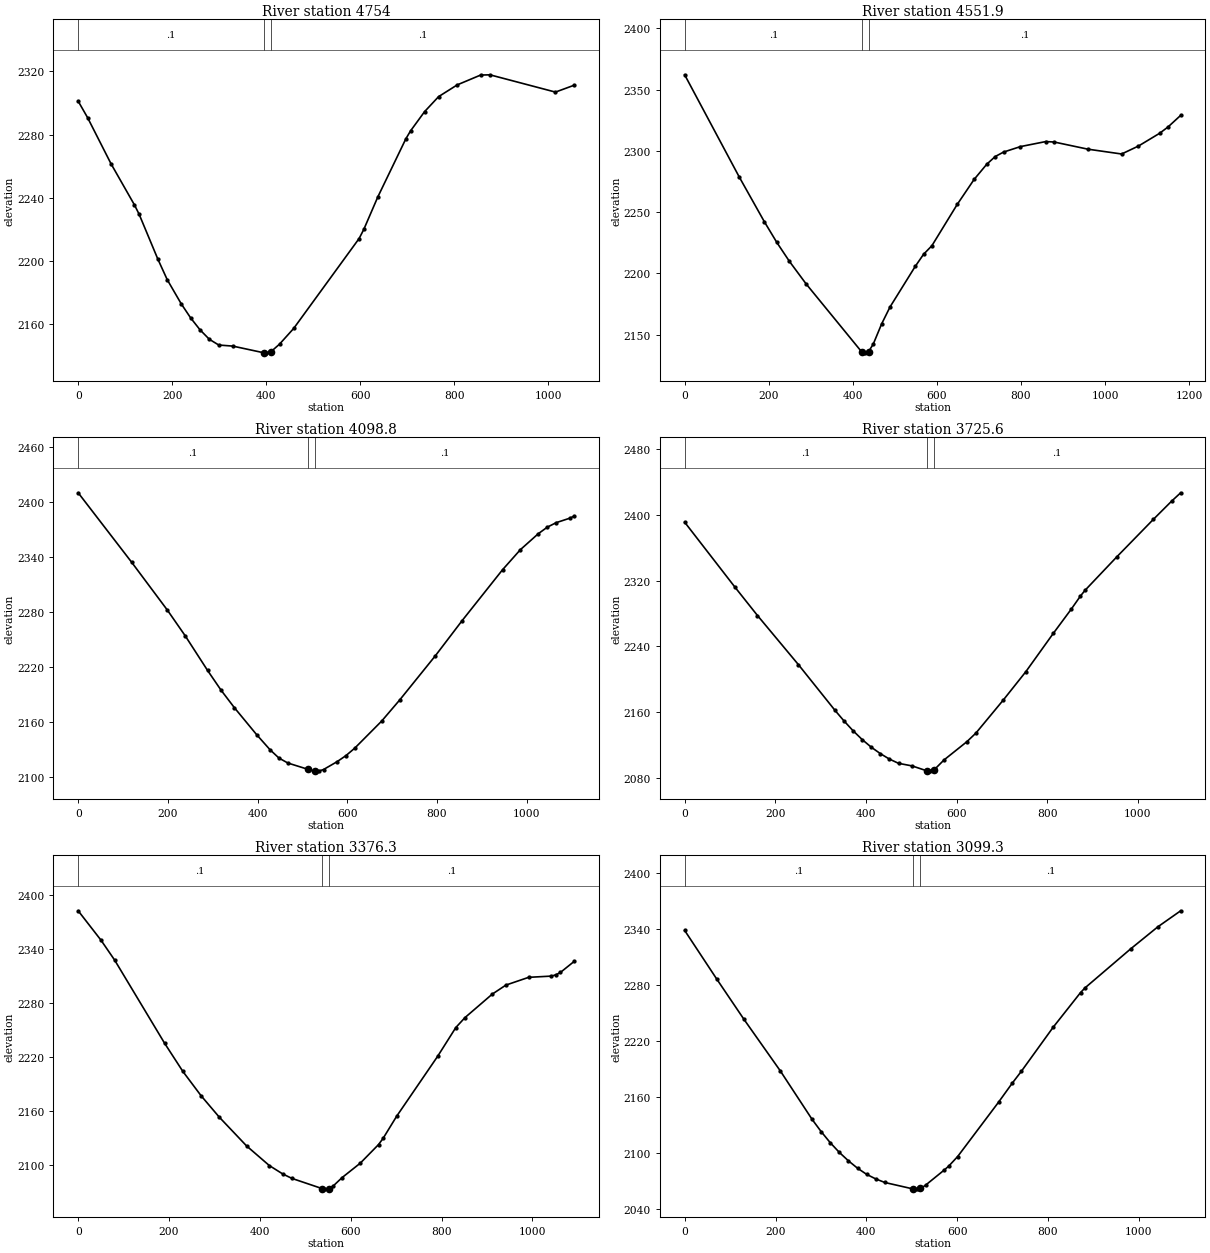
Type RM Length L Ch R = 1 ,4754    ,226.2,202,177.9
XS GIS Cut Line= 3
     2181102.745      365455.782     2181346.762      365867.226
     2181812.543      366207.619
#Sta/Elev= 30
       0 2301.04    19.9 2290.71    69.8 2261.54   119.6 2235.57   129.6 2229.65
   169.4 2201.32   189.4  2188.3   219.2 2173.04   239.2 2164.15   259.1 2156.64
     279 2150.63     299    2147   328.9 2146.32   394.4 2142.13   398.6 2141.88
   409.4 2142.59   428.5 2147.59   458.4 2157.45   597.7 2214.29   607.7 2220.06
   637.5 2240.57   697.2 2277.32   707.1 2282.29     737 2294.46   766.8 2303.95
   806.6  2311.4   856.3  2317.6   876.2 2317.74  1015.5 2306.83  1055.3 2311.17
#Mann= 3 , 0 , 0
       0      .1       0   394.4    .045       0   409.4      .1       0
Bank Sta=394.4,409.4
XS Rating Curve= 0 ,0
Exp/Cntr=0.3,0.1

Type RM Length L Ch R = 1 ,4551.9  ,455.1,453.2,450.8
XS GIS Cut Line= 3
     2180794.607      365974.095     2181382.652      365959.243
     2181882.067      366276.541
#Sta/Elev= 30
       0 2361.98   129.6 2278.73   189.4 2242.17   219.3 2225.14   249.2 2209.73
   289.1 2191.26   418.7 2136.88   422.6 2136.08   428.7 2134.84   437.6 2136.16
   448.6 2142.17   468.6  2158.7   488.5 2172.49   548.4 2205.56   568.3  2215.5
   588.2 2222.53   648.4 2256.21   688.5 2276.56   718.6 2288.98   738.7 2295.27
   758.7 2298.94   798.8  2303.4     859 2307.51   879.1 2307.14   959.3  2301.3
  1039.5 2297.36  1079.6 2303.86  1129.8 2314.23  1149.8 2319.38  1179.9 2328.85
#Mann= 3 , 0 , 0
       0      .1       0   422.6    .045       0   437.6      .1       0
Bank Sta=422.6,437.6
XS Rating Curve= 0 ,0
Exp/Cntr=0.3,0.1

Type RM Length L Ch R = 1 ,4098.8  ,364.9,373.2,381.4
XS GIS Cut Line= 3
     2180834.422      366458.658     2181476.527      366381.681
     2181920.766      366498.657
#Sta/Elev= 30
       0 2410.18   119.4 2334.37     199 2282.24   238.8 2254.21   288.5 2216.58
   318.4 2195.19   348.2 2176.04     398 2146.54   427.8 2130.15   447.7 2121.07
   467.6 2115.65   513.4 2108.64   527.3 2106.82   528.4 2106.84   537.3 2106.99
   547.2 2108.59   577.1 2117.03     597 2123.68   616.8 2131.87   676.7 2161.32
   716.6 2184.14   796.5 2232.54   856.4 2270.97   946.3 2326.28   986.2 2348.23
  1026.2 2365.64  1046.2 2372.75  1066.1 2377.67  1096.1 2382.48  1106.1 2384.84
#Mann= 3 , 0 , 0
       0      .1       0   513.4    .045       0   528.4      .1       0
Bank Sta=513.4,528.4
XS Rating Curve= 0 ,0
Exp/Cntr=0.3,0.1

Type RM Length L Ch R = 1 ,3725.6  ,344.8,349.2,353.6
XS GIS Cut Line= 2
     2180810.426      366630.903     2181872.091      366895.697
#Sta/Elev= 30
       0 2390.89   110.4 2312.36   160.6 2277.55     251 2217.81   331.3 2162.53
   351.3  2149.6   371.4  2137.6   391.5 2126.89   411.6 2117.58   431.6 2109.78
   451.7 2103.09   471.8 2097.96   501.9 2094.78     534 2088.88   542.1 2088.47
     549 2090.22   552.1    2091   572.2 2102.06   622.4 2124.13   642.5 2134.66
   702.7 2174.68   752.9 2209.43   813.1 2255.69   853.3 2285.56   873.3 2301.28
   883.4  2308.2   953.6 2348.92    1034 2394.31  1074.1 2416.34  1094.2  2426.6
#Mann= 3 , 0 , 0
       0      .1       0     534    .045       0     549      .1       0
Bank Sta=534,549
XS Rating Curve= 0 ,0
Exp/Cntr=0.3,0.1

Type RM Length L Ch R = 1 ,3376.3  ,271.2,277,282.9
XS GIS Cut Line= 2
     2180729.003      366861.287     2181718.147      367323.951
#Sta/Elev= 30
       0 2382.69    50.1 2350.04    80.2 2327.82   190.4 2235.04   230.4 2203.82
   270.5 2176.76   310.6 2152.88   370.7 2120.84   420.8 2098.96   450.8 2089.46
   470.9 2084.59   536.6 2073.37     541  2072.7   551.6 2073.25     561 2076.01
   581.1 2085.57   621.1 2101.63   661.2 2122.29   671.2 2129.15   701.3 2153.98
   791.4 2220.62   831.5 2252.72   851.6 2263.75   911.7 2289.91   941.7 2299.97
   991.8 2308.61  1041.9 2309.99  1051.9 2311.43  1061.9 2314.11    1092 2326.35
#Mann= 3 , 0 , 0
       0      .1       0   536.6    .045       0   551.6      .1       0
Bank Sta=536.6,551.6
XS Rating Curve= 0 ,0
Exp/Cntr=0.3,0.1

Type RM Length L Ch R = 1 ,3099.3  ,247.1,247.4,247.7
XS GIS Cut Line= 2
     2180704.923      367008.797     2181541.492      367710.664
#Sta/Elev= 30
       0 2338.03    70.1 2286.41   130.2  2243.2   210.4 2187.94   280.5    2136
   300.6 2122.81   320.6 2110.97   340.6  2100.6   360.7 2091.56   380.7  2083.7
   400.7 2077.14   420.8 2072.25   440.8 2068.44   503.6 2061.47   510.9 2061.35
   518.6  2062.1     521 2062.34     531 2065.82     571 2081.58   581.1 2085.82
   601.1 2096.24   691.3 2154.47   721.3  2174.7   741.4 2187.43   811.5  2234.6
   871.6 2271.55   881.6 2276.66   981.8 2318.25  1041.9 2341.94    1092 2359.03
#Mann= 3 , 0 , 0
       0      .1       0   503.6    .045       0   518.6      .1       0
Bank Sta=503.6,518.6
XS Rating Curve= 0 ,0
Exp/Cntr=0.3,0.1

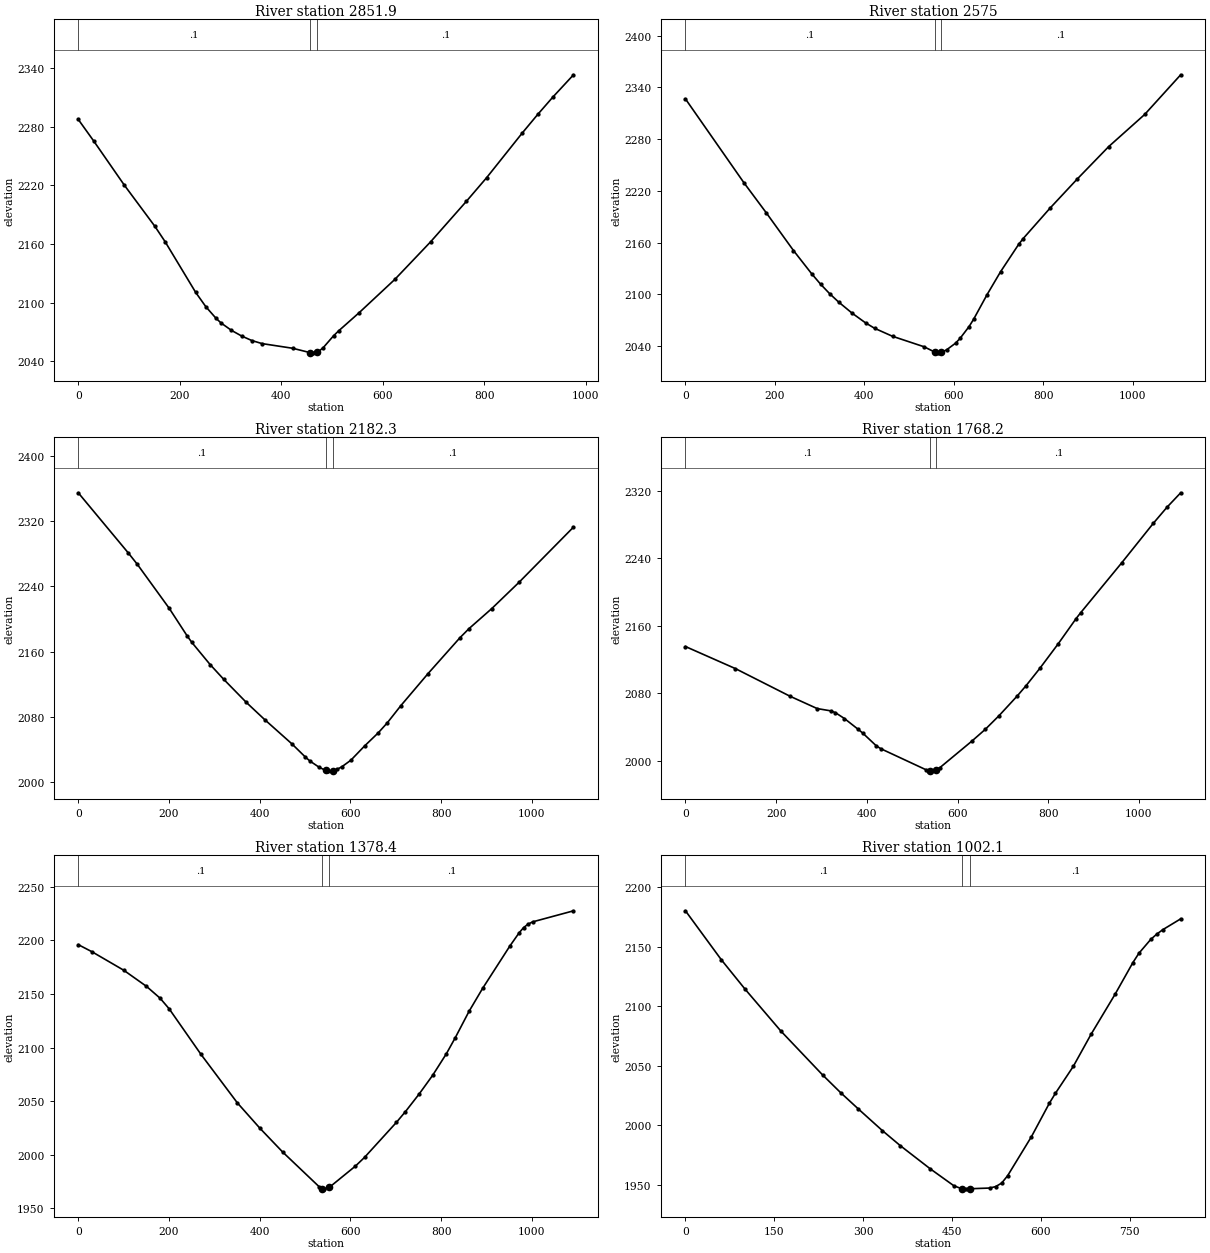
Type RM Length L Ch R = 1 ,2851.9  ,270.3,276.9,283.4
XS GIS Cut Line= 2
     2180595.295      367231.865     2181334.816      367868.196
#Sta/Elev= 30
       0 2287.42    30.2 2265.54    90.5  2220.4   150.9 2178.14     171 2162.47
   231.3 2110.55   251.4 2095.85   271.6 2083.93   281.6 2079.18   301.7 2071.76
   321.8 2065.97     342 2061.32   362.1 2058.21   422.4 2053.43   455.9 2049.08
   462.7 2048.47   470.9 2049.54   472.7 2049.77   482.8 2054.21   502.9 2066.19
     513 2071.28   553.2 2089.77   623.6 2123.86     694 2162.25   764.4 2203.61
   804.6 2227.98     875 2273.81   905.2 2292.63   935.4  2310.6   975.6  2333.1
#Mann= 3 , 0 , 0
       0      .1       0   455.9    .045       0   470.9      .1       0
Bank Sta=455.9,470.9
XS Rating Curve= 0 ,0
Exp/Cntr=0.3,0.1

Type RM Length L Ch R = 1 ,2575    ,387.3,392.8,398.2
XS GIS Cut Line= 2
     2180455.084      367263.452     2181055.223      368194.267
#Sta/Elev= 30
       0 2326.68   130.9 2229.36   181.2 2194.28   241.6 2150.84   281.9 2124.14
     302 2111.93   322.2 2100.94   342.3 2091.23   372.5 2078.29   402.7 2066.99
   422.9 2060.68   463.1 2051.38   533.6 2039.24   557.3 2033.15   563.8 2031.86
   572.3 2032.74     584 2035.68   604.1 2043.43   614.2 2049.02   634.3 2062.68
   644.4 2071.09   674.6 2099.76   704.8 2126.33     745 2157.86   755.1 2164.64
   815.5 2200.09   875.9 2233.62   946.4 2271.32    1027 2308.65  1107.5 2354.64
#Mann= 3 , 0 , 0
       0      .1       0   557.3    .045       0   572.3      .1       0
Bank Sta=557.3,572.3
XS Rating Curve= 0 ,0
Exp/Cntr=0.3,0.1

Type RM Length L Ch R = 1 ,2182.3  ,420.5,414,407.7
XS GIS Cut Line= 2
     2180213.193      367343.718     2180568.283      368376.424
#Sta/Elev= 30
       0 2354.33   110.2 2280.76   130.2 2266.78   200.4    2213   240.4 2178.85
   250.5  2171.1   290.6 2144.13   320.6 2126.04   370.7 2097.63   410.8 2076.76
   470.9 2047.03   500.9 2030.72     511 2025.86     531 2018.36   545.6 2014.42
     551 2013.58   560.6 2013.98   571.1 2015.94   581.1 2018.88   601.1 2026.96
   631.2 2044.32   661.2 2060.31   681.3 2072.64   711.3 2093.78   771.4 2133.09
   841.6 2176.91   861.6 2188.07   911.7 2212.56   971.8  2244.7    1092 2312.34
#Mann= 3 , 0 , 0
       0      .1       0   545.6    .045       0   560.6      .1       0
Bank Sta=545.6,560.6
XS Rating Curve= 0 ,0
Exp/Cntr=0.3,0.1

Type RM Length L Ch R = 1 ,1768.2  ,390.4,389.8,389.1
XS GIS Cut Line= 2
     2179709.578      367607.609     2180339.812      368499.621
#Sta/Elev= 30
       0 2135.56   110.2 2109.43   230.5 2076.76   290.6 2062.12   320.6 2059.42
   330.7 2057.29   350.7 2050.31   380.8 2037.63   390.8 2033.22   420.8 2018.08
   430.9 2014.61   531.1 1989.58   538.5 1988.48   541.1  1988.1   551.1 1988.93
   553.5 1989.72   561.1 1992.21   631.3 2023.45   661.3 2037.56   691.4 2053.61
   731.5  2076.9   751.5  2089.4   781.6 2109.74   821.6  2138.4   861.7 2168.73
   871.8 2175.65   961.9 2234.44  1032.1 2281.53  1062.1 2300.44  1092.2 2317.47
#Mann= 3 , 0 , 0
       0      .1       0   538.5    .045       0   553.5      .1       0
Bank Sta=538.5,553.5
XS Rating Curve= 0 ,0
Exp/Cntr=0.3,0.1

Type RM Length L Ch R = 1 ,1378.4  ,374,376.3,378.5
XS GIS Cut Line= 2
     2179383.548      367848.381     2180038.749       368721.98
#Sta/Elev= 30
       0 2196.09    30.1 2189.49   100.2 2172.23   150.3 2157.21   180.3 2146.16
   200.4 2136.22   270.5 2093.75   350.6 2048.55   400.7 2024.71   450.8 2002.56
     531 1970.29   538.5 1968.57     541    1968   553.5 1969.64   611.1 1989.48
   631.2 1997.61   701.3 2030.18   721.3 2040.26   751.4 2056.61   781.4 2074.17
   811.5 2094.18   831.5 2109.43   861.6 2133.82   891.6  2155.3   951.7 2194.82
   971.8 2206.95   981.8 2211.96   991.8 2215.22  1001.8 2217.35    1092 2227.66
#Mann= 3 , 0 , 0
       0      .1       0   538.5    .045       0   553.5      .1       0
Bank Sta=538.5,553.5
XS Rating Curve= 0 ,0
Exp/Cntr=0.3,0.1

Type RM Length L Ch R = 1 ,1002.1  ,407,402.2,397.5
XS GIS Cut Line= 2
     2179163.447      368099.593     2179595.272      368814.921
#Sta/Elev= 30
       0 2180.08    60.4 2139.02   100.7 2114.16   161.1 2078.97   231.5 2042.09
   261.7 2027.31   291.9 2013.46   332.2 1995.38   362.4 1982.74   412.8 1963.32
     453 1948.95   465.8 1946.56   473.2 1946.16   480.8 1946.49   513.4 1947.07
   523.5 1948.32   533.6 1951.26   543.6 1957.42   583.9 1990.32   614.1 2018.41
   624.2 2026.66   654.4 2049.32   684.6 2076.47   724.8 2109.84     755 2136.57
   765.1 2144.39   785.2  2156.1   795.3  2160.5   805.4 2164.21   835.6 2173.32
#Mann= 3 , 0 , 0
       0      .1       0   465.8    .045       0   480.8      .1       0
Bank Sta=465.8,480.8
XS Rating Curve= 0 ,0
Exp/Cntr=0.3,0.1

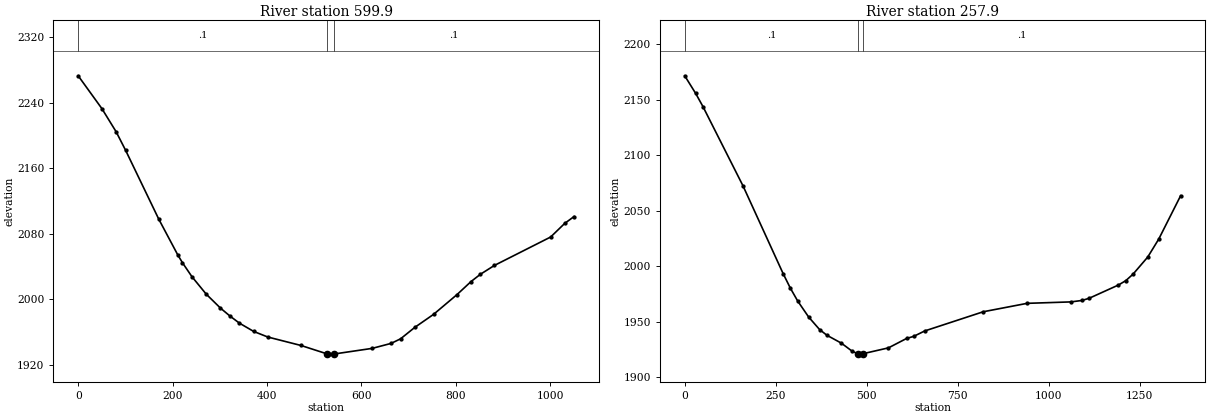
Type RM Length L Ch R = 1 ,599.9   ,348.1,342,335.8
XS GIS Cut Line= 3
     2178677.801      368252.911     2179163.447      368775.493
     2179488.254      368867.491
#Sta/Elev= 30
       0 2272.92    50.2 2232.86    80.4 2204.57   100.5 2181.92   170.8 2097.78
     211 2054.21     221 2044.57   241.2 2027.45   271.3 2006.27   301.4 1989.27
   321.5 1979.57   341.6 1970.86   371.8 1960.74   401.9 1953.87   472.2 1943.56
   527.9 1933.21   532.5 1932.99   542.9  1933.2     623 1940.01   663.2 1946.11
   683.3 1951.71   713.4 1965.68   753.1 1981.54   802.8 2005.69   832.6 2021.64
   852.4 2030.52   882.2 2041.35  1001.3 2076.04  1031.1 2092.65    1051 2101.08
#Mann= 3 , 0 , 0
       0      .1       0   527.9    .045       0   542.9      .1       0
Bank Sta=527.9,542.9
XS Rating Curve= 0 ,0
Exp/Cntr=0.3,0.1

Type RM Length L Ch R = 1 ,257.9   ,269.3,257.9,246.6
XS GIS Cut Line= 4
     2178536.362      368482.603     2178714.724      368829.941
     2178917.494      368955.733     2179642.944         369061.
#Sta/Elev= 30
       0 2171.57      30 2155.74    50.1 2143.81   160.2  2072.3   270.3 1993.29
   290.3 1980.11   310.4 1968.55   340.4 1954.18   370.4 1942.92   390.5 1937.77
   430.2 1930.66     460 1923.35     476 1921.01   479.9 1920.76     491 1921.24
   559.5  1926.4   609.2 1934.85   629.1  1936.8   659.2 1941.65   819.9 1958.94
   940.4 1966.53  1060.9 1967.83    1091 1969.12  1111.1 1971.13  1191.4 1983.06
  1211.5 1986.98  1231.6  1992.9  1271.8 2008.26  1301.9 2024.38  1362.1 2063.51
#Mann= 3 , 0 , 0
       0      .1       0     476    .045       0     491      .1       0
Bank Sta=476,491
XS Rating Curve= 0 ,0
Exp/Cntr=0.3,0.1

Chan Stop Cuts=-1
Use User Specified Reach Order=0
Composite Channel Slope=5